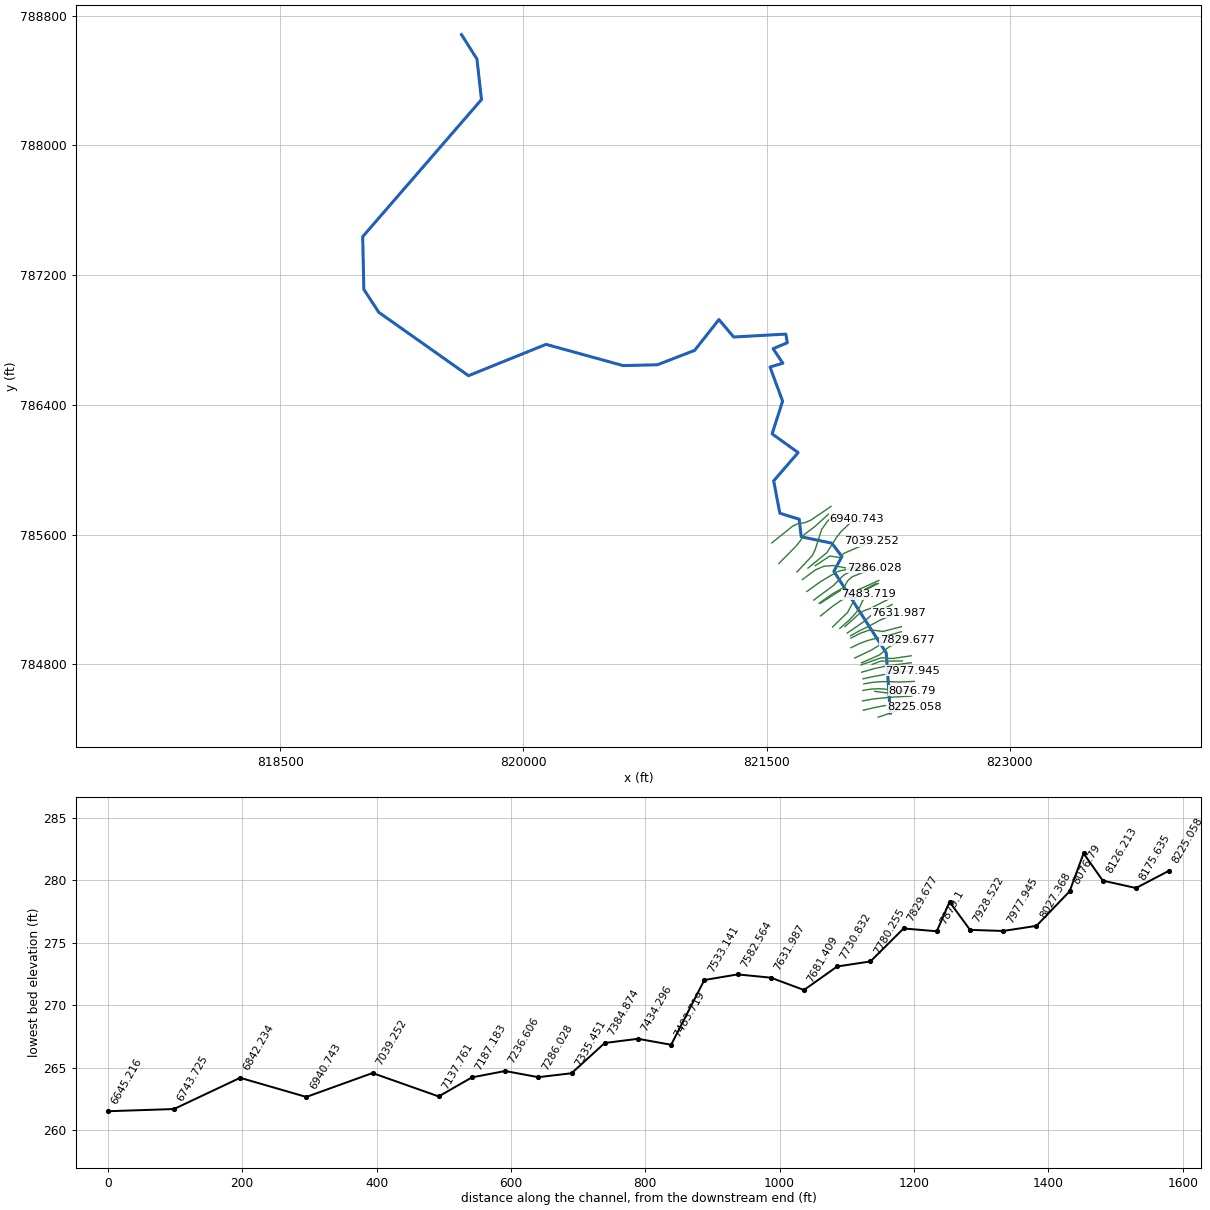
--- 17398_ras.prj (project) ---

Proj Title=17398
Current Plan=p01
Default Exp/Contr=0.3,0.1
English Units
Geom File=g01
Flow File=f01
Plan File=p01
Y Axis Title=Elevation
X Axis Title(PF)=Main Channel Distance
X Axis Title(XS)=Station
BEGIN DESCRIPTION:
RFD model 17398 exported to HEC-RAS
END DESCRIPTION:

--- 17398_ras.p01 (plan) ---

Plan Title=Plan 01
Program Version=4.10
Short Identifier=Plan 01
Geom File=g01
Flow File=f01
Subcritical Flow
Calc Critical at every XS
Secant Critical Depth

--- 17398_ras.f01 (steady flow) ---

Flow Title=Flow 01
Program Version=5.01
Number of Profiles= 6
Profile Names=10yr,25yr,50yr,100yr,100plus,500yr
River Rch & RM=17398,49,8225.058
  144.97  234.21  318.14  395.81  577.89  1037.3
River Rch & RM=17398,49,8027.368
  148.11  239.32  325.12  404.55  590.64 1057.15
River Rch & RM=17398,49,  7879.1
     152  245.67  333.81  415.42  606.51 1081.77
River Rch & RM=17398,49,7780.255
  156.64  253.25  344.18  428.38  625.43 1111.01
River Rch & RM=17398,49,7631.987
  158.19  255.77  347.62  432.68  631.72  1120.7
River Rch & RM=17398,49,7483.719
  198.82  322.05  438.33  546.09  797.29 1371.13
River Rch & RM=17398,49,7286.028
  206.84  335.17  456.29  568.56  830.09 1419.91
River Rch & RM=17398,49,7137.761
  210.11   340.5  463.59   577.7  843.44 1439.67
River Rch & RM=17398,49,6940.743
  217.64  352.82  480.49  598.86  874.33 1485.38
River Rch & RM=17398,49,6743.725
  218.35  353.99   482.1  600.87  877.27  1489.7
River Rch & RM=17398,49,6645.216
  219.78  356.33  485.31  604.89  883.14 1498.33
River Rch & RM=17398,49,6546.707
  223.68  362.71  494.07  615.87  899.17 1521.98
River Rch & RM=17398,49,6448.198
   226.5  367.34  500.42  623.83  910.79 1539.08
River Rch & RM=17398,49, 6251.18
   227.9  369.64  503.58   627.8  916.58  1547.6
River Rch & RM=17398,49,6152.671
  237.44  385.24  524.97  654.57  955.67 1604.67
River Rch & RM=17398,49,6054.162
  239.19  388.11   528.9   659.5  962.87 1615.15
River Rch & RM=17398,49,5857.144
  241.96  392.65  535.15  667.34  974.31 1631.86
River Rch & RM=17398,49,5660.126
     243  394.36  537.49  670.28  978.61 1638.11
River Rch & RM=17398,49,5561.617
  248.19  402.87  549.18  684.93    1000 1669.22
River Rch & RM=17398,49,5463.108
  249.22  404.56  551.51  687.85 1004.26 1675.42
River Rch & RM=17398,49,4994.185
  250.25  406.25  553.83  690.77 1008.52  1681.6
Boundary for River Rch & Prof#=17398,49,1
Up Type= 0
Dn Type= 2
Boundary for River Rch & Prof#=17398,49,2
Up Type= 0
Dn Type= 2
Boundary for River Rch & Prof#=17398,49,2
Up Type= 0
Dn Type= 2
Boundary for River Rch & Prof#=17398,49,2
Up Type= 0
Dn Type= 2
Boundary for River Rch & Prof#=17398,49,2
Up Type= 0
Dn Type= 2
Boundary for River Rch & Prof#=17398,49,2
Up Type= 0
Dn Type= 2

--- 17398_ras.g01 (geometry) ---

Geom Title=17398
Program Version=4.10

River Reach=17398,49
Reach XY= 30
822262.833405613784498.901985561822238.043839574784869.925727636
821914.975067946 785373.58686676821964.545494677785464.645585423
 821902.04365224785547.083360324821713.709954858785586.507862291
821701.067900419785694.717022548821581.666282536785731.812650022
 821543.73567641785931.254167482821694.602192551786105.828279009
821534.037114681 786221.13340208821598.653548123786422.941912999
821521.105699033786633.322276494821600.310620009786657.029871884
821539.964013517786746.472163614821627.789878278 786783.11117467
821618.630125492786836.453264296821297.176484944786818.495092036
821205.981922421786925.785795478821056.190879285786736.051562732
820826.835669252786647.357004069820615.312215897786642.150272922
820139.807243944786773.105475088819661.684672087786579.972219451
819108.193024813786970.949297925819016.336964222787112.266314219
819009.271113399787437.295451769819741.764314683788282.842266064
819713.786720127788532.585178536819618.539129018788683.493929047

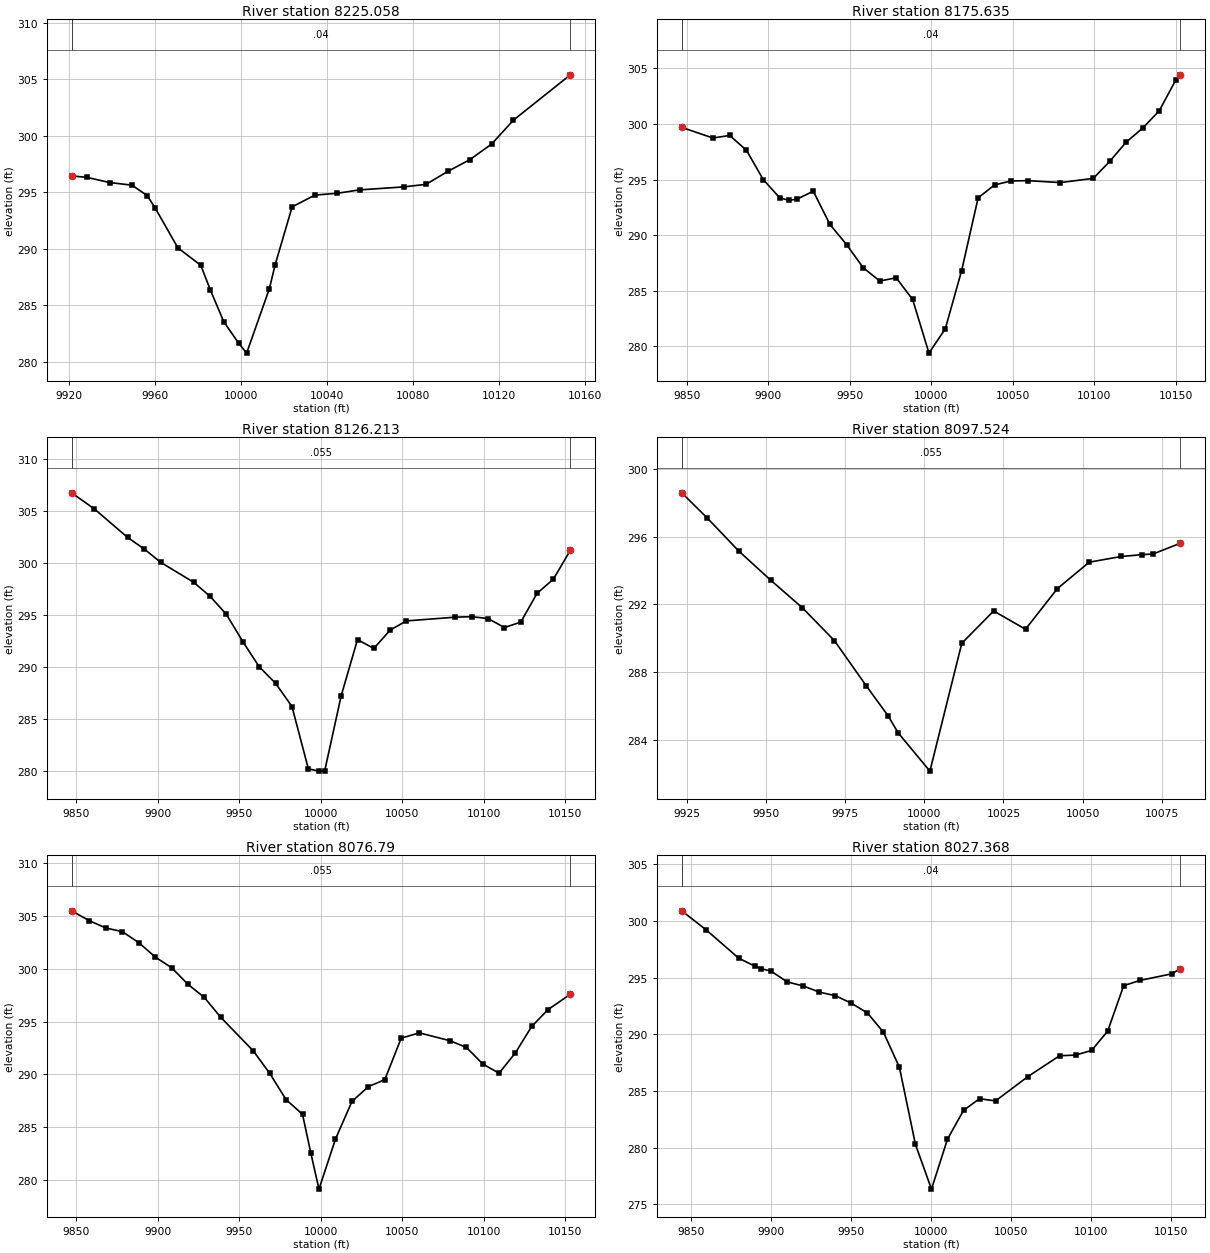
Type RM Length L Ch R = 1 ,8225.058,49.422600,49.422600,49.422600
XS GIS Cut Line= 6
822188.173243897784474.347619655  822215.4566073784482.761732569
822263.393816146784500.200423097 822301.75530471784513.213275278
822346.838672638784523.908958152822410.986496305784535.236119967
#Sta/Elev= 25
9921.437296.44729928.581296.31219939.046295.85789949.511295.62299956.557294.6972
9960.139293.64069970.776 290.0849981.412288.53979985.904286.34089992.049283.5681
    9999281.6549 10002.7280.777310013.26286.473610015.94288.591210023.82293.7045
10034.38294.745110044.84294.909610055.12295.206410075.68295.471910085.95295.6963
10096.13296.842510106.29297.875710116.44299.256410126.59301.375110152.98 305.378
#Mann= 3 , 0 , 0
9921.437    0.04       09921.437    0.04       010152.98    0.04       0
#XS Ineff= 2 , 0
       0                               0
Bank Sta=9921.437,10152.98
Exp/Cntr=0.3,0.1

Type RM Length L Ch R = 1 ,8175.635,49.422600,49.422600,49.422600
XS GIS Cut Line= 6
822096.430977249 784516.81666264822160.375545072784532.284525979
822215.304181317784543.171744675822235.709623906784545.889285314
 822262.90238038784547.120173893822397.934981004784566.259374943
#Sta/Elev= 30
9847.004299.68849866.109298.73389876.397298.96519886.686297.63319896.974294.9984
9907.263293.32859912.793 293.1399917.508293.22199927.702293.94639937.897290.9612
9948.091289.15269958.286287.0749 9968.48285.87029978.572286.1585 9988.66284.2102
 9998.67279.383710008.69281.574310018.73286.811910028.83293.348210038.93294.5169
10049.03 294.86810059.13294.898510079.33294.725910099.53 295.10410109.63296.6421
10119.73298.370110129.83299.628810139.93301.176410150.03303.929710152.99304.4173
#Mann= 3 , 0 , 0
9847.004    0.04       09847.004    0.04       010152.99    0.04       0
#XS Ineff= 2 , 0
       0                               0
Bank Sta=9847.004,10152.99
Exp/Cntr=0.3,0.1

Type RM Length L Ch R = 1 ,8126.213,28.688400,28.688400,28.688400
XS GIS Cut Line= 6
822091.220066756784574.389698302822155.303500318784585.990486583
822241.691858428784595.006030972822243.672311439784595.284968014
822255.321079287 784596.73062809822395.378813923784604.141663031
#Sta/Elev= 28
9847.017306.70989861.021305.15899881.346302.42949891.509301.32189901.672300.0303
9921.892298.11839931.946296.7689    9942295.02789952.055292.41949962.109290.0019
9972.163288.40729982.217286.17989992.272280.19169998.942279.973110002.34280.0294
10012.41287.214510022.43292.609610032.44291.756910042.46293.525610052.47294.4053
10082.51294.764610092.53294.811910102.54294.629610112.56293.768310122.57294.2869
10132.58297.0525 10142.6298.413410152.99301.1854
#Mann= 3 , 0 , 0
9847.017   0.055       09847.017   0.055       010152.99   0.055       0
#XS Ineff= 2 , 0
       0                               0
Bank Sta=9847.017,10152.99
Exp/Cntr=0.3,0.1

Type RM Length L Ch R = 1 ,8097.524,20.734200,20.734200,20.734200
XS GIS Cut Line= 2
822167.111842513784633.126694039822323.633545518784613.482269779
#Sta/Elev= 19
9923.236298.58129931.186297.11649941.264295.14689951.342293.42979961.421  291.79
9971.499289.86169981.578287.19379988.495285.42259991.656284.420910001.73282.1551
10011.81289.701110021.89291.607710031.97290.529610042.05 292.92810052.13294.4861
10062.21294.8232 10068.8294.929810072.28294.971210080.99295.6087
#Mann= 3 , 0 , 0
9923.236   0.055       09923.236   0.055       010080.99   0.055       0
#XS Ineff= 2 , 0
       0                               0
Bank Sta=9923.236,10080.99
Exp/Cntr=0.3,0.1

Type RM Length L Ch R = 1 , 8076.79,49.422600,49.422600,49.422600
XS GIS Cut Line= 6
822094.218968867784639.353382233822140.521355118 784646.74614913
822186.189327212784649.602704575822220.295262512784647.811272743
822306.052088503784636.891164115822398.673334187784638.350050239
#Sta/Elev= 30
 9847.04305.48569857.958304.54569868.085303.85849878.211 303.5099888.338302.4626
9898.417301.09799908.436300.09129918.456 298.5219928.475297.27569938.495295.4042
9958.523292.21089968.537290.09969978.592287.60269988.693286.20899993.762282.5606
9998.794279.119110008.92283.857310019.04287.425810029.15288.834510039.19289.4901
10049.23293.418610060.33293.924710079.27293.175610089.28 292.54210099.28290.9749
10109.28290.100910119.29292.0297 10129.3294.533310139.31296.124210152.99297.5815
#Mann= 3 , 0 , 0
 9847.04   0.055       0 9847.04   0.055       010152.99   0.055       0
#XS Ineff= 2 , 0
       0                               0
Bank Sta=9847.04,10152.99
Exp/Cntr=0.3,0.1

Type RM Length L Ch R = 1 ,8027.368,49.422600,49.422600,49.422600
XS GIS Cut Line= 6
822099.952431207784679.619436373 822149.01545914784688.113687645
822199.874014043784692.758475679822238.177912988784693.449168118
822320.924582122784690.912663807822410.468912661784694.632011935
#Sta/Elev= 29
9844.207300.90739859.478299.22249879.776296.73279889.924 296.022    9894295.7934
9900.009295.59049910.051294.63559920.092294.27929930.134293.73659940.175293.4191
9950.197292.75489960.198291.8961  9970.2   290.29980.201287.0959 9990.21280.2951
10000.23276.354210010.23 280.76710020.24283.296110030.24284.332510040.24284.1348
10060.25286.261710080.26288.123610090.27288.177410100.28288.591910110.29 290.291
 10120.3294.2981 10130.3294.762910150.32 295.348 10155.8295.8108
#Mann= 3 , 0 , 0
9844.207    0.04       09844.207    0.04       0 10155.8    0.04       0
#XS Ineff= 2 , 0
       0                               0
Bank Sta=9844.207,10155.8
Exp/Cntr=0.3,0.1

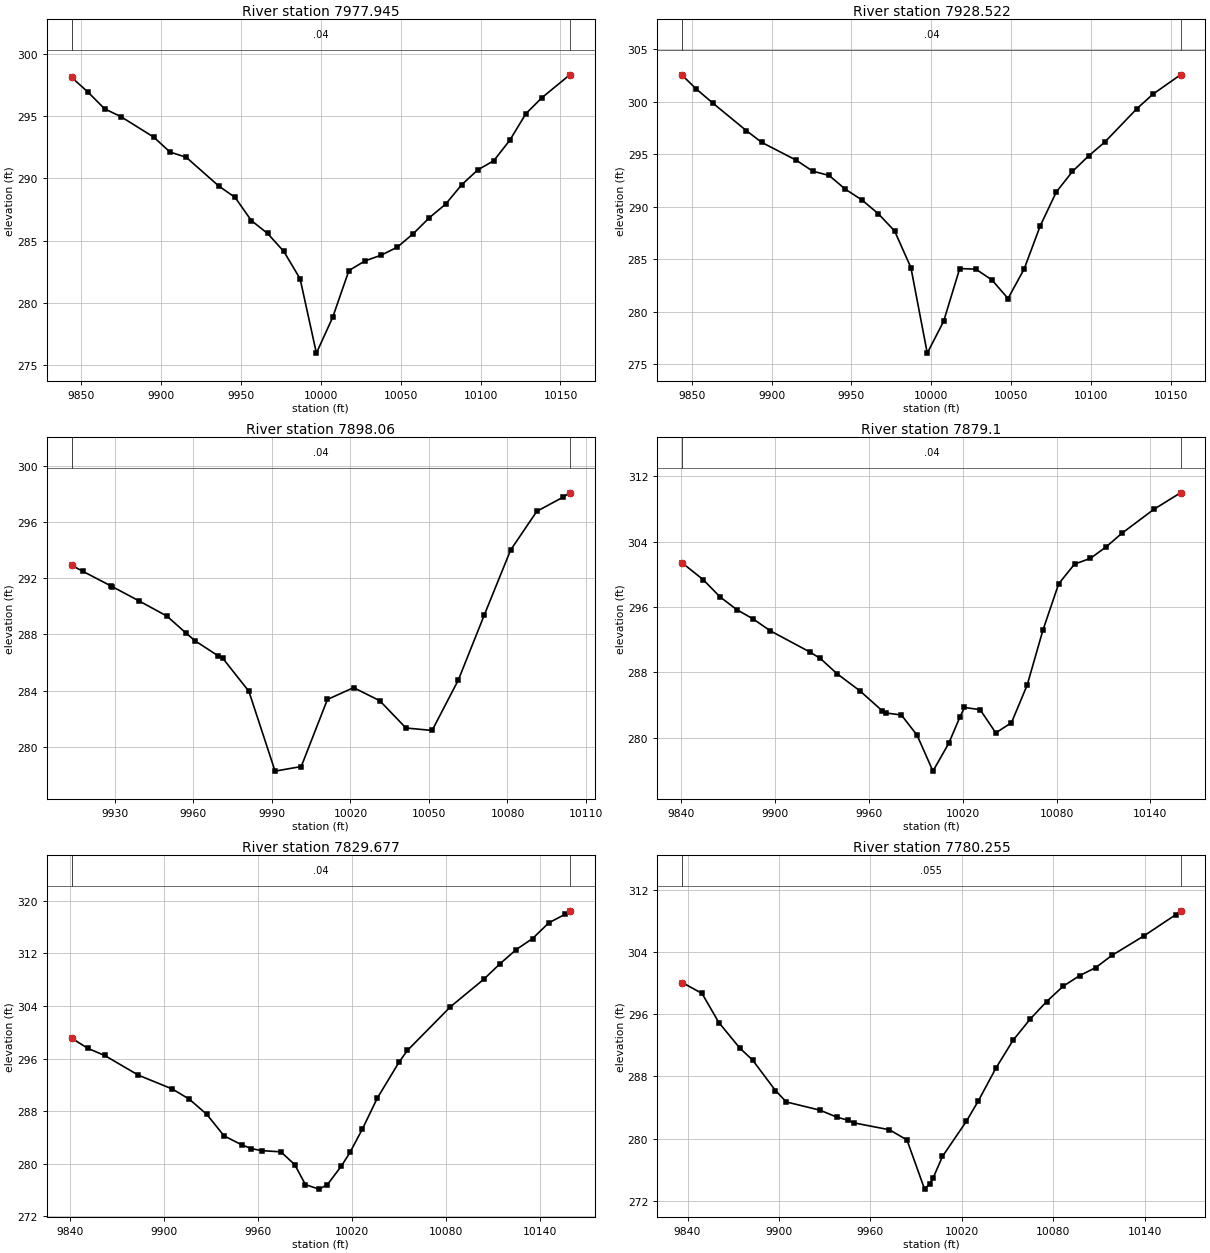
Type RM Length L Ch R = 1 ,7977.945,49.422700,49.422700,49.422700
XS GIS Cut Line= 6
822094.854681209784710.697256838822143.357193988784721.586399946
822246.655439252784741.014690043822248.613249099784741.423322645
822275.834147894784746.429471718822402.260827994784759.798718139
#Sta/Elev= 29
9844.181298.13229854.579296.92549864.828295.60119875.076294.96759895.562293.3228
9905.738292.12429915.913291.69829936.264 289.3879946.439 288.4759956.614 286.611
 9966.79285.57229976.965 284.123 9987.14281.92139997.316275.945410007.49278.8172
10017.66282.589810027.83283.370410037.89283.828410047.95284.472710058.01285.5666
10068.06286.849410078.12287.925710088.17 289.48510098.23290.684910108.28291.4233
10118.34293.0812 10128.4295.214610138.45296.501410155.81298.3338
#Mann= 3 , 0 , 0
9844.181    0.04       09844.181    0.04       010155.81    0.04       0
#XS Ineff= 2 , 0
       0                               0
Bank Sta=9844.181,10155.81
Exp/Cntr=0.3,0.1

Type RM Length L Ch R = 1 ,7928.522,30.461800,30.461800,30.461800
XS GIS Cut Line= 6
822086.555489216784751.417898527822166.408273388 784774.13600562
822236.557593263784789.394731721 822238.51540311784789.803364323
822245.013679511784791.099775732822392.020642542784809.763671977
#Sta/Elev= 28
9844.189302.51049852.968301.21139863.365299.86039884.159297.25639893.824296.1289
9915.349294.43769925.746 293.3849936.003292.97259946.237291.65399956.471290.6459
9966.704289.33479976.938287.69119987.172 284.1959997.406276.033910007.63279.0581
10017.69284.093610027.77284.042110037.85283.011810047.93281.241410058.01284.0576
10068.09288.175310078.17291.406810088.25293.356310098.33294.834410108.42296.1475
10128.58299.349810138.66300.734710155.81302.5668
#Mann= 3 , 0 , 0
9844.189    0.04       09844.189    0.04       010155.81    0.04       0
#XS Ineff= 2 , 0
       0                10023.57       0
Bank Sta=9844.189,10155.81
Exp/Cntr=0.3,0.1

Type RM Length L Ch R = 1 , 7898.06,18.960800,18.960800,18.960800
XS GIS Cut Line= 3
 822150.95271939784799.470609143822203.232235551784819.431878954
822337.574749798784820.699261159
#Sta/Elev= 24
9913.491292.91239917.823292.47889928.527 291.4439928.992291.39629939.231290.3818
9949.935289.29549957.027288.1205 9960.64287.54449969.452286.47749971.219286.3086
 9981.22283.9512 9991.22278.276210001.22278.602210011.22283.370110021.22284.2106
10031.22283.281710041.22281.341810051.22281.168910061.22284.752410071.22289.4116
10081.22294.001310091.22296.749910101.23297.7527 10103.8298.0629
#Mann= 3 , 0 , 0
9913.491    0.04       09913.491    0.04       0 10103.8    0.04       0
#XS Ineff= 2 , 0
       0                 10023.6       0
Bank Sta=9913.491,10103.8
Exp/Cntr=0.3,0.1

Type RM Length L Ch R = 1 ,  7879.1,49.422600,49.422600,49.422600
XS GIS Cut Line= 6
  822082.4887028784796.155624133822202.833570483784839.069809467
 822220.27119467784840.503152284822251.988580332784836.026569825
822280.808204078784836.382031796822391.883531882784852.713719155
#Sta/Elev= 30
9840.776301.39089854.157299.34619864.852297.25149875.547295.69299886.242294.5199
9896.937293.10429922.122290.51929929.022289.70969939.572287.8597 9954.34285.7409
9968.612 283.2999970.785283.04049980.819282.79289990.878280.3106   10001275.9205
 10011.1279.320710018.15282.498810021.16283.708910031.16283.445710041.16280.6006
10051.19281.844310061.26286.464210071.33 293.187 10081.4298.851910091.51301.2526
10101.64301.959310111.77303.3735 10121.9 305.04510142.16307.949410159.26309.9791
#Mann= 3 , 0 , 0
9840.776    0.04       09840.776    0.04       010159.26    0.04       0
#XS Ineff= 2 , 0
       0                10025.77       0
Bank Sta=9840.776,10159.26
Exp/Cntr=0.3,0.1

Type RM Length L Ch R = 1 ,7829.677,49.422600,49.422600,49.422600
XS GIS Cut Line= 6
822085.478609985784808.892968552822196.533195639784857.922568971
822242.485087215784898.403640629822268.176837239784914.455645787
822304.891705496784929.437103628 822367.81560755784947.979661321
#Sta/Elev= 30
9840.752299.10019851.057297.55579861.881296.46779883.528293.46399905.175291.3626
9915.998289.81859927.112287.5276 9938.24284.23849949.368282.8972 9955.54282.3123
9962.202281.99839974.536281.81689983.382279.8673 9990.25276.8224    9999276.1464
10004.27 276.83110013.28279.675210018.73281.738810026.61285.2666 10036.1289.9478
 10050.2295.501410055.38297.219810082.91303.864210104.13308.025210114.56310.3981
10124.98312.560710135.41314.238410145.83316.630110156.26317.9307 10159.2318.4515
#Mann= 3 , 0 , 0
9840.752    0.04       09840.752    0.04       0 10159.2    0.04       0
#XS Ineff= 2 , 0
       0                               0
Bank Sta=9840.752,10159.2
Exp/Cntr=0.3,0.1

Type RM Length L Ch R = 1 ,7780.255,49.422600,49.422600,49.422600
XS GIS Cut Line= 6
822043.311521088784838.843826892822141.385392028784885.269836665
822221.001721946784932.856887995 822244.37307226784944.971969376
822281.618878364  784959.9099255822337.972478069784977.818801062
#Sta/Elev= 30
9836.566300.05359849.498298.65749860.562294.90999874.327291.6288 9882.69 290.092
9897.699286.17379904.817284.71119926.945283.64859938.009282.75629945.074282.3704
9949.254282.01689972.387281.13739983.953279.8319 9995.52273.5046    9999274.2216
   10001274.878110007.22 277.69910022.96282.229210030.77284.842110042.49289.1169
 10053.6292.645710064.84295.369410075.61297.619410086.39 299.57610097.16300.9407
10107.84301.985810118.33303.535710139.32306.0416 10160.3308.779610163.42309.2765
#Mann= 3 , 0 , 0
9836.566   0.055       09836.566   0.055       010163.42   0.055       0
#XS Ineff= 2 , 0
       0                               0
Bank Sta=9836.566,10163.42
Exp/Cntr=0.3,0.1

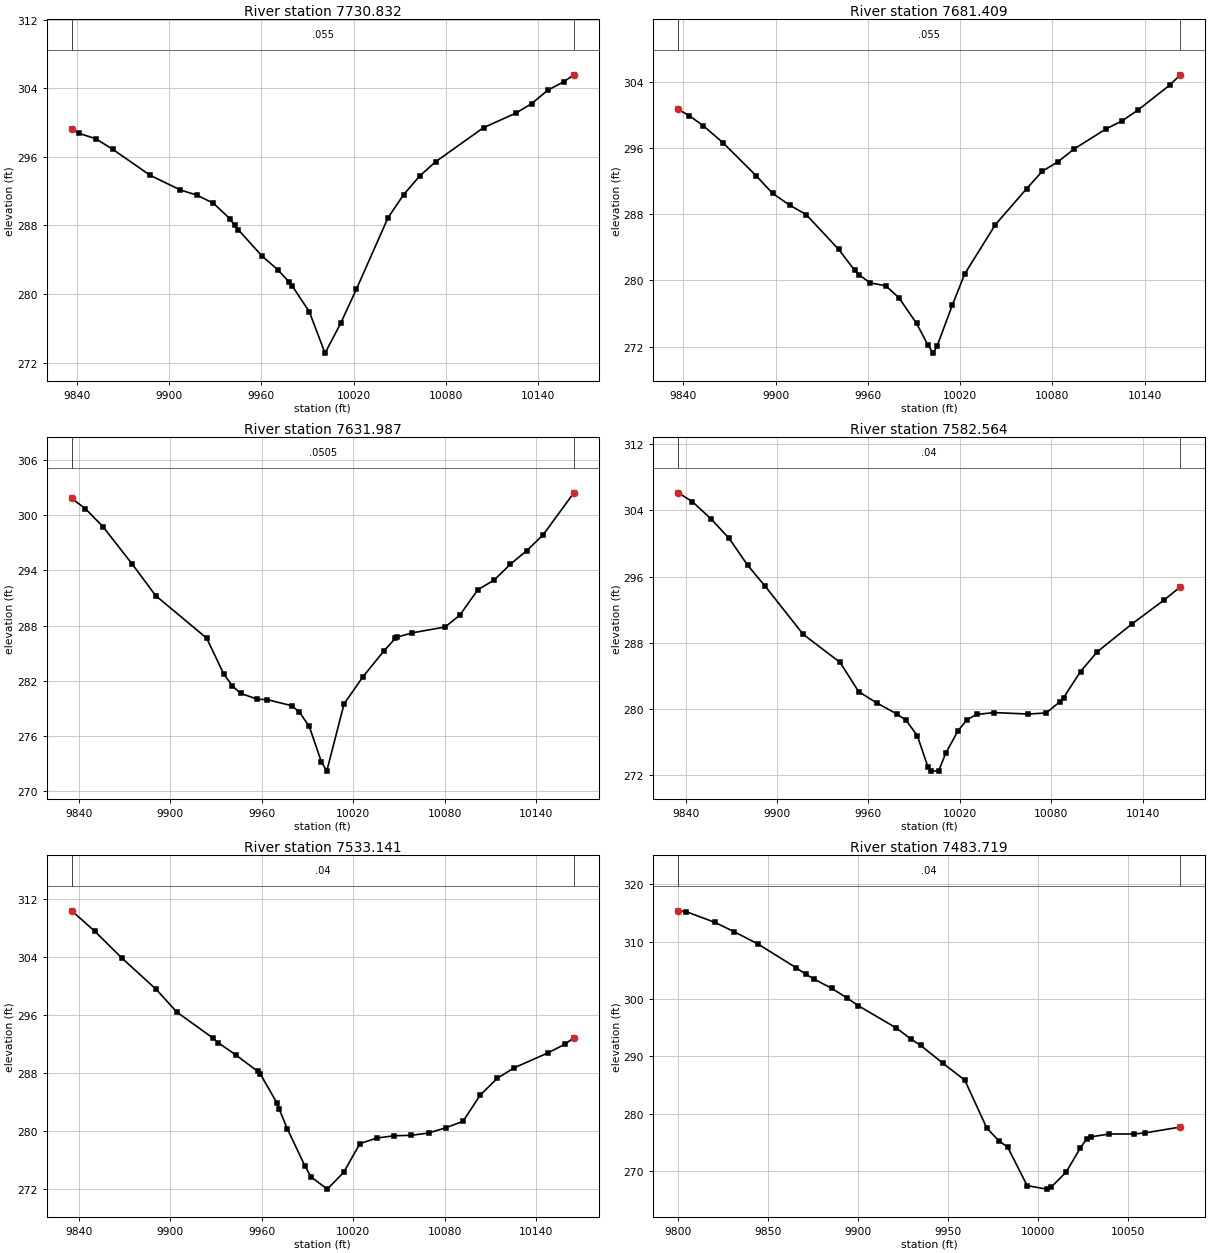
Type RM Length L Ch R = 1 ,7730.832,49.422600,49.422600,49.422600
XS GIS Cut Line= 6
822020.887714901784902.747717475822072.488755435784927.729578262
822120.303983028784945.895708877822152.278652215784954.592648946
822227.114620125784970.722652487822331.381019808 785001.38820511
#Sta/Elev= 29
9836.588299.19719841.157298.75499852.267298.11199863.377 296.8659887.654293.8433
9907.302292.13669917.999291.53949928.697290.60289939.394288.80899942.546288.0192
9945.068287.48089960.298284.45639970.661282.83889978.204 281.3779980.125280.9386
9991.222277.932510001.45273.102710011.68276.597210021.91280.575410042.37288.8648
 10052.6291.587810062.98293.7493 10073.4295.423410104.67299.409610125.52301.0862
10135.94302.205210146.37303.762810156.79304.755810163.44305.5709
#Mann= 3 , 0 , 0
9836.588   0.055       09836.588   0.055       010163.44   0.055       0
#XS Ineff= 2 , 0
       0                               0
Bank Sta=9836.588,10163.44
Exp/Cntr=0.3,0.1

Type RM Length L Ch R = 1 ,7681.409,49.422600,49.422600,49.422600
XS GIS Cut Line= 6
822020.464492654784961.682721777822080.569564287784992.768205193
 822127.94903862785009.038463943822153.438255802785011.361782921
822216.808551729785002.708581884822331.517117945785031.936784347
#Sta/Elev= 30
9836.703300.65599843.924299.89179853.067298.67349865.692296.6526 9887.46292.6316
  9898.1290.51429909.127289.10389919.864287.96259941.089283.74419951.467281.2207
9954.528280.65099961.608279.6986 9971.65279.36079980.123277.93319991.721274.8103
    9999272.239610002.53271.2182 10005.2272.129710015.04277.038310023.01 280.774
10043.02286.744910063.36291.088810073.54293.192510083.74294.333210094.13295.8714
10114.93298.299510125.33 299.26310135.72300.576310156.52303.608410163.29304.8352
#Mann= 3 , 0 , 0
9836.703   0.055       09836.703   0.055       010163.29   0.055       0
#XS Ineff= 2 , 0
       0                               0
Bank Sta=9836.703,10163.29
Exp/Cntr=0.3,0.1

Type RM Length L Ch R = 1 ,7631.987,49.422700,49.422700,49.422700
XS GIS Cut Line= 6
  822017.2228776 784975.36287993822069.421510869785005.154751352
822137.780997738785038.426623941822198.115890385785071.607284501
822243.957591754785091.214748571 822314.00585443785117.315525051
#Sta/Elev= 30
9835.196 301.7979844.151300.68549855.665 298.7379874.812294.69069890.207291.2633
9923.746286.63969934.867 282.7839940.645281.45479945.989280.6466 9957.11280.0113
9963.495 279.9659979.618279.30449984.682278.60989991.105277.0513    9999 273.247
10002.59272.206210013.95279.502210026.22282.420110040.19285.269410047.67286.6295
10048.81286.744810058.55287.2087 10080.3287.850410090.05 289.15210101.83 291.903
 10112.5292.943210123.17294.666810133.84296.130510144.52297.8256 10164.8302.4096
#Mann= 3 , 0 , 0
9835.196  0.0505       09835.196  0.0505       0 10164.8  0.0505       0
#XS Ineff= 2 , 0
       0                               0
Bank Sta=9835.196,10164.8
Exp/Cntr=0.3,0.1

Type RM Length L Ch R = 1 ,7582.564,49.422600,49.422600,49.422600
XS GIS Cut Line= 6
 821997.44145434784992.819376469822102.057594679785064.786211453
822138.333526724785096.931816806822155.086651507785108.756471156
822208.598814238785138.151384899822274.570368296785168.253163116
#Sta/Elev= 30
9835.191306.11829844.365305.06669856.503303.0054 9868.64300.59819880.778297.3535
9891.971 294.8969917.191289.00969941.466285.61049953.604282.07919965.937 280.667
9978.738279.37369984.801 278.613 9992.15276.7386    9999273.0262   10001272.5137
10006.11 272.467 10010.7274.601810018.86277.339410024.69278.6766 10031.1279.3246
10042.51279.546710064.94279.369710076.74279.502210085.71280.851510088.15281.3536
10099.29284.513110110.28286.901810132.84290.237110154.25293.176110164.77294.7444
#Mann= 3 , 0 , 0
9835.191    0.04       09835.191    0.04       010164.77    0.04       0
#XS Ineff= 2 , 0
       0                               0
Bank Sta=9835.191,10164.77
Exp/Cntr=0.3,0.1

Type RM Length L Ch R = 1 ,7533.141,49.422600,49.422600,49.422600
XS GIS Cut Line= 6
821983.828405352785032.869292919822065.342112168785106.526494104
822086.158994541785122.492453341822101.190831369785130.408250904
  822138.8178483785144.364528118822260.332897603785206.038100416
#Sta/Elev= 30
9835.249310.39479850.306307.58539868.258303.86329890.739299.54649904.217296.4314
9927.919 292.8519931.173292.23029942.835290.53759957.283288.25649959.035287.8799
9969.886283.91449971.346283.07599976.728280.32849988.335275.19519992.366273.6895
10002.94272.018310013.66274.316810024.38278.296310035.47279.060210046.79279.3755
 10058.1279.440510069.42279.757310080.73280.477310092.05281.374310103.37284.9969
10114.56287.302910125.63288.750110147.79290.805810158.87291.993310164.78292.8909
#Mann= 3 , 0 , 0
9835.249    0.04       09835.249    0.04       010164.78    0.04       0
#XS Ineff= 2 , 0
       0                               0
Bank Sta=9835.249,10164.78
Exp/Cntr=0.3,0.1

Type RM Length L Ch R = 1 ,7483.719,49.422600,49.422600,49.422600
XS GIS Cut Line= 6
821951.784031959785021.486177431822008.437322187785071.492708941
822049.183863961 785115.47902164 822073.67307305785150.548607129
822091.615898948785192.180517303822130.301367437785231.581745649
#Sta/Elev= 30
9799.959315.35539804.248 315.222 9820.38313.33879830.925311.73429844.264309.5754
9865.714305.3962 9870.94304.30199875.525303.44089885.182301.86389893.937300.1433
9899.897298.8434  9921.2294.93479929.327293.00359934.831291.87579947.097288.7914
9959.293285.8378 9971.49277.51479978.258275.23699983.099274.17889993.975267.4442
10004.79266.833910007.42 267.21210015.74269.836510023.61274.038110027.07275.6028
10029.45275.951810039.56276.436610053.23 276.45410059.33276.627510079.14277.6576
#Mann= 3 , 0 , 0
9799.959    0.04       09799.959    0.04       010079.14    0.04       0
#XS Ineff= 2 , 0
       0                               0
Bank Sta=9799.959,10079.14
Exp/Cntr=0.3,0.1

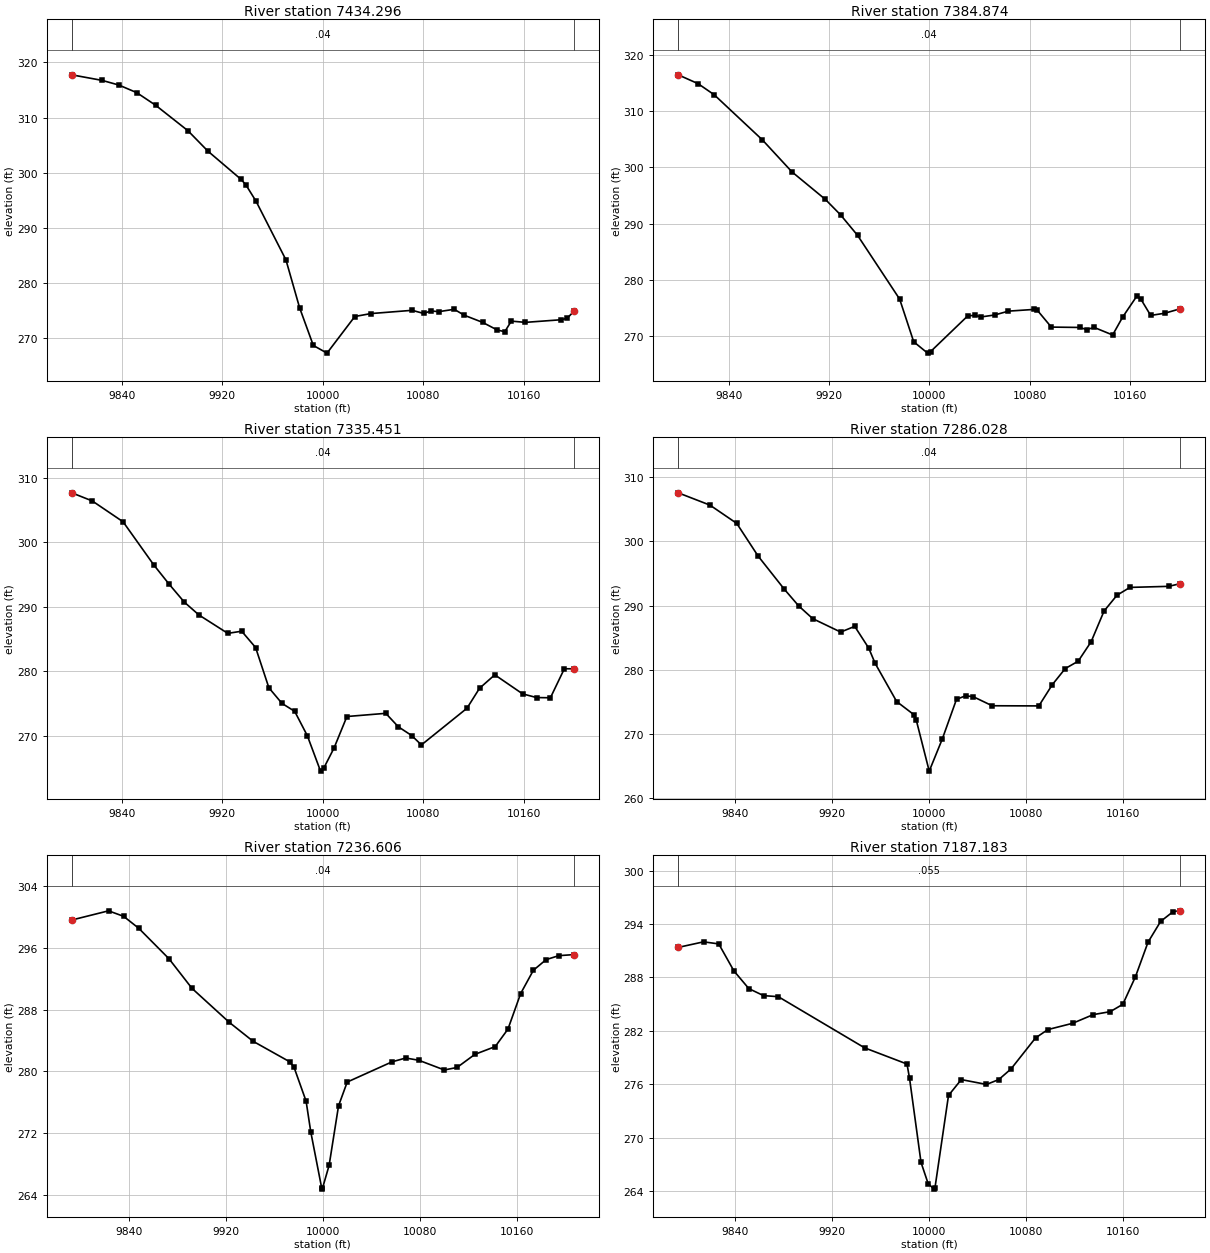
Type RM Length L Ch R = 1 ,7434.296,49.422600,49.422600,49.422600
XS GIS Cut Line= 6
821906.959204255785030.584123393821999.325152118785119.704476104
822043.889284383785203.699199154822057.332871899785220.653699951
822112.117101958785259.225656951822189.739356183785299.508047206
#Sta/Elev= 30
9799.926317.75319824.056316.74789837.432315.90499851.747314.52029866.805312.2306
 9892.55 307.6159908.428303.92299934.785298.8181  9938.7297.80569946.783 294.847
 9970.61284.21769981.519275.52729992.427268.706110003.34267.312210025.51273.9484
10038.27  274.4810071.21 275.07210080.37274.503510086.25274.967910092.25274.8211
10104.76275.257210112.59274.192110127.34272.888710138.78271.529710145.01271.1863
10150.22273.116210161.36272.885910189.85273.362210194.79273.634310200.07274.8927
#Mann= 3 , 0 , 0
9799.926    0.04       09799.926    0.04       010200.07    0.04       0
#XS Ineff= 2 , 0
       0                 10032.2       0
Bank Sta=9799.926,10200.07
Exp/Cntr=0.3,0.1

Type RM Length L Ch R = 1 ,7384.874,49.422600,49.422600,49.422600
XS GIS Cut Line= 6
821832.622893678785098.346829142821910.336215382785160.505280928
821960.868782427785195.052275496821992.589214916785210.949450487
822051.397947944785233.144859636822176.139714637785299.124967104
#Sta/Elev= 30
9799.861316.4836 9815.71314.90639828.515312.94029866.931304.91269890.561299.2123
9917.138294.32599929.252291.57839942.777287.94159976.395276.5789 9987.58268.9971
9998.656266.9761   10001267.237510030.69273.6067 10036.4273.700610041.41273.4179
10052.13273.7609 10063.1274.447510083.68274.753310085.89274.662410097.29271.6082
10120.09271.543410125.34271.160810131.49271.543510146.17270.204710154.15273.3852
10165.33277.0762 10168.5276.6489 10176.5273.681310187.68 274.07210200.13274.8703
#Mann= 3 , 0 , 0
9799.861    0.04       09799.861    0.04       010200.13    0.04       0
#XS Ineff= 2 , 0
       0                10032.93       0
Bank Sta=9799.861,10200.13
Exp/Cntr=0.3,0.1

Type RM Length L Ch R = 1 ,7335.451,49.422700,49.422700,49.422700
XS GIS Cut Line= 6
821831.705292468785176.885687518821955.983414727785255.886613422
821987.517514163785263.589183996822027.398637158785252.597316341
822055.260845817785254.853607025822191.838824124785317.419690722
#Sta/Elev= 30
9799.927307.66059816.257306.40459840.824 303.173 9865.39296.46899877.673293.4744
9889.635 290.7299901.286288.74059924.277285.89329935.361286.22419946.444   283.7
9957.038277.45999967.494275.03939977.589273.81759987.685270.03559998.204264.5521
   10001265.102310008.95268.124910019.23273.0119 10050.2273.505210060.18271.4257
10070.85270.0647 10078.6268.610410114.92274.293410124.95277.391310137.09279.4702
10159.26276.519410170.35275.948510181.43275.913910192.52280.4083 10200.1280.4061
#Mann= 3 , 0 , 0
9799.927    0.04       09799.927    0.04       0 10200.1    0.04       0
#XS Ineff= 2 , 0
       0                10019.23       0
Bank Sta=9799.927,10200.1
Exp/Cntr=0.3,0.1

Type RM Length L Ch R = 1 ,7286.028,49.422600,49.422600,49.422600
XS GIS Cut Line= 6
821824.041772319 785176.19841651821902.987304357785232.508313059
821977.876192198785275.468965958 822000.19828352785315.464743592
822027.528254947785339.593621289822163.950000042 785394.70831597
#Sta/Elev= 30
9793.143307.54679819.272305.63529841.374302.78829859.029297.68829880.471 292.568
9892.455289.93859903.983 287.9679927.041285.87839938.569286.76879950.098283.3944
9955.432281.00329973.155 275.068 9987.19273.04759989.227272.23889999.982264.2398
10010.76269.242710022.47275.416410029.94275.959610036.24 275.82510051.86 274.413
10090.32274.387410101.42277.694810112.08280.200610122.74281.3439 10133.4284.3692
10144.07289.150310154.73291.613310165.39292.829510197.37292.994210206.91293.4154
#Mann= 3 , 0 , 0
9793.143    0.04       09793.143    0.04       010206.91    0.04       0
#XS Ineff= 2 , 0
       0                               0
Bank Sta=9793.143,10206.91
Exp/Cntr=0.3,0.1

Type RM Length L Ch R = 1 ,7236.606,49.422600,49.422600,49.422600
XS GIS Cut Line= 6
821790.636294947785195.988968078821914.219209729785287.541607559
821966.128520226785341.563855709821984.729341855785356.317472826
822021.128509406785372.964543808822136.793120879785409.712991292
#Sta/Elev= 30
9792.974299.60439823.295300.7953 9835.74300.08199848.185 298.5369873.076294.5946
9892.108290.74769922.856286.34329942.505283.88969972.539281.24739976.148280.5679
9986.209276.12379990.046272.1516    9999264.91999999.515264.731910005.19267.8225
10012.94275.5208 10020.1278.607710057.14281.231510068.33281.720710079.05281.4345
10100.18280.173410110.67280.497210125.37282.196210142.15283.202910152.64285.4664
10163.13290.078910173.62 293.09510184.12294.472310194.61294.987710206.98295.1212
#Mann= 3 , 0 , 0
9792.974    0.04       09792.974    0.04       010206.98    0.04       0
#XS Ineff= 2 , 0
       0                               0
Bank Sta=9792.974,10206.98
Exp/Cntr=0.3,0.1

Type RM Length L Ch R = 1 ,7187.183,49.422600,49.422600,49.422600
XS GIS Cut Line= 6
821748.318198577785249.190106494821834.394203699785311.121022903
821935.714335407785370.751340913821959.395063947785378.300867892
822044.700239517785393.061060844822120.584991529785414.686091601
#Sta/Elev= 30
9792.946291.37529813.833291.99879826.354291.76679838.875288.73089851.175286.7442
9863.318285.9563 9875.46285.83989946.699280.08839981.594 278.273  9983.7276.6659
9993.149267.2291    9999264.851710003.95264.221310004.59264.303610015.82274.7462
10026.36276.525710047.14 275.98110057.26276.526910067.37277.7218 10087.6281.2082
10097.77 282.14310118.17282.848710135.15283.824410149.18284.156410159.58284.9834
10169.97288.074510180.37291.962210190.77294.296510201.17 295.40410206.98295.4827
#Mann= 3 , 0 , 0
9792.946   0.055       09792.946   0.055       010206.98   0.055       0
#XS Ineff= 2 , 0
       0                               0
Bank Sta=9792.946,10206.98
Exp/Cntr=0.3,0.1

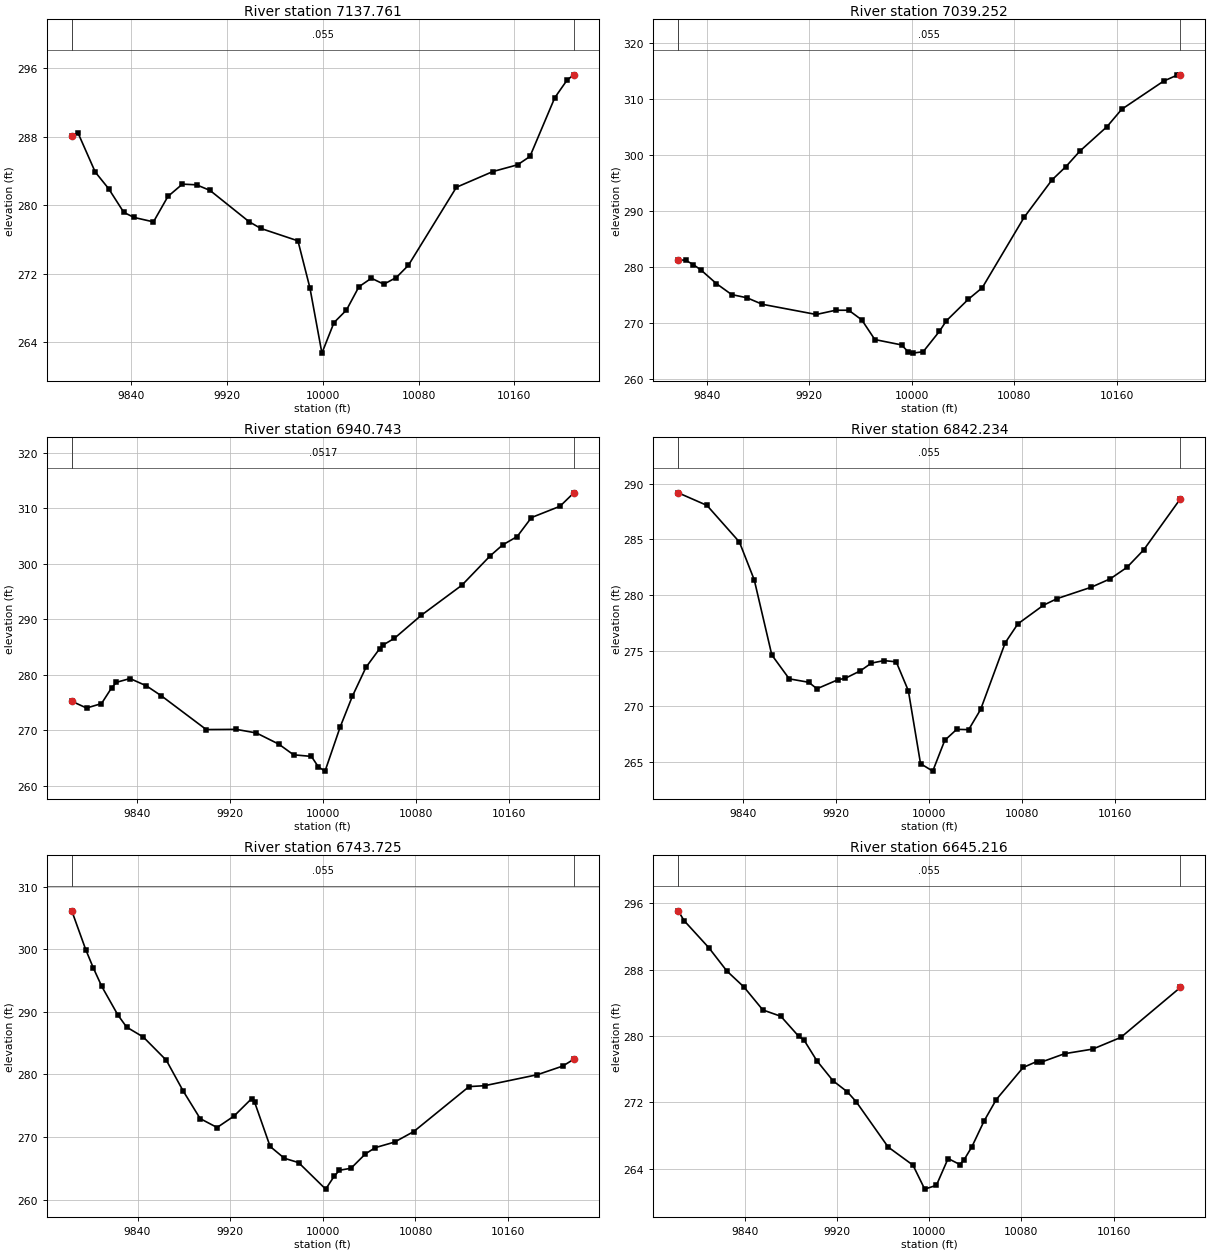
Type RM Length L Ch R = 1 ,7137.761,98.509000,98.509000,98.509000
XS GIS Cut Line= 6
821720.828434492785322.894974805821801.870607857 785382.55618786
821854.189369144785405.089477231821912.831408928785409.219543892
822000.736672328785391.706942898822110.357316547 785415.60475004
#Sta/Elev= 30
9790.259 288.0969795.562288.39719809.864283.85569820.987281.9273  9833.7279.1472
9842.255278.55279858.489278.03519870.571281.00669882.652 282.4469894.466282.3634
9905.692281.71449938.427278.0483 9948.09277.27269979.177275.81799989.181270.3124
9999.185262.697410009.28266.266210019.68267.730910030.09270.4508 10040.5271.4505
 10050.9270.752910061.31271.531510071.41272.958210111.52282.078710141.96283.9146
10162.58284.701210172.95285.677710193.69292.544710204.06294.624410209.61295.2174
#Mann= 3 , 0 , 0
9790.259   0.055       09790.259   0.055       010209.61   0.055       0
#XS Ineff= 2 , 0
       0                               0
Bank Sta=9790.259,10209.61
Exp/Cntr=0.3,0.1

Type RM Length L Ch R = 1 ,7039.252,98.509000,98.509000,98.509000
XS GIS Cut Line= 6
821800.245191723785408.581169799821890.099736415785467.953904213
821950.997467218785458.340921062821966.768916835785476.641222446
821982.633243895785486.986033206822147.026535208785557.577769915
#Sta/Elev= 30
9817.868281.20139823.567281.15639829.512280.38819835.553279.42019847.539276.9974
9859.525275.02419871.511274.44879883.497273.28569925.567271.46879940.747272.2236
9950.935272.22289961.123270.50059971.311266.99089992.167266.03419997.364264.7887
   10001264.569310009.05 264.825 10021.7268.456810027.18270.352210044.27274.1848
10055.16276.244310087.81288.803710109.57295.488710120.45297.864110131.34300.6313
 10152.5304.992610163.99308.095310196.63313.113510207.52314.220410209.72314.2447
#Mann= 3 , 0 , 0
9817.868   0.055       09817.868   0.055       010209.72   0.055       0
#XS Ineff= 2 , 0
       0                               0
Bank Sta=9817.868,10209.72
Exp/Cntr=0.3,0.1

Type RM Length L Ch R = 1 ,6940.743,98.508900,98.508900,98.508900
XS GIS Cut Line= 6
821755.151493813785393.365593957821871.475338303785487.956822601
821932.595587447785584.374344414821958.722264427785618.102789416
822006.849464375785663.767446427822054.717837474785697.939028846
#Sta/Elev= 30
9783.887275.25119796.581274.0305 9809.47274.82429818.178277.66299822.359278.6633
9834.028279.34059848.137278.02819861.026276.22989899.692270.1462 9925.47270.1831
9942.838269.53419962.188267.51389974.837265.59729990.194265.30919996.295263.3955
10001.95262.6557 10014.9 270.56710025.48276.152910037.25281.390110049.07 284.752
10052.21285.422510061.72286.600910084.87290.755110119.74296.158710144.09301.4498
10154.88303.426210167.36304.933610179.65308.353710204.22310.390810216.16312.8134
#Mann= 3 , 0 , 0
9783.887  0.0517       09783.887  0.0517       010216.16  0.0517       0
#XS Ineff= 2 , 0
       09955.034                       0
Bank Sta=9783.887,10216.16
Exp/Cntr=0.3,0.1

Type RM Length L Ch R = 1 ,6842.234,98.509000,98.509000,98.509000
XS GIS Cut Line= 6
821687.275643508785369.337711853821780.994064988785469.602125271
821799.409476195785506.633314264821839.719333605785632.231068509
821875.209355851785681.674498821821918.303474798785723.660300152
#Sta/Elev= 30
9783.809 289.1819808.546288.0515 9836.46284.76679849.265281.36539864.374274.6218
9879.386272.47529896.216272.16589903.221271.58349921.333272.3956 9927.57272.5236
9940.647273.19549950.099 273.8879960.985274.11359971.516274.00269981.978271.4004
 9992.44264.858110002.96264.1875 10013.3266.951410023.59267.940110033.89 267.912
10044.19269.726210065.35275.712110076.23277.410410098.25 279.08510110.08279.6814
10139.51 280.70710155.92281.4648 10170.2 282.48810184.58284.051310216.13288.6356
#Mann= 3 , 0 , 0
9783.809   0.055       09783.809   0.055       010216.13   0.055       0
#XS Ineff= 2 , 0
       09983.976                       0
Bank Sta=9783.809,10216.13
Exp/Cntr=0.3,0.1

Type RM Length L Ch R = 1 ,6743.725,98.509000,98.509000,98.509000
XS GIS Cut Line= 6
821576.336024782785422.151525592821679.785333625785526.662826879
821706.523207198785559.673927082821732.985141787785600.810593799
821796.938564408785649.047145601821882.089023835785726.130396061
#Sta/Elev= 30
9783.196 306.143 9795.22299.96329801.725297.05569809.098  294.079822.977289.5129
9830.568287.5694 9844.99285.97899864.837282.27559879.453277.34449894.069272.9542
9908.685271.53139923.302273.36059938.581276.15729941.025275.61079954.469268.5061
9966.762266.61649979.045265.924810002.45261.687710009.82263.753710014.38 264.705
 10024.3265.017910036.82 267.32610045.34268.318310061.94 269.20210078.55270.8902
10126.24278.064610139.73278.210710185.25279.965210207.17 281.34610216.74282.4391
#Mann= 3 , 0 , 0
9783.196   0.055       09783.196   0.055       010216.74   0.055       0
#XS Ineff= 2 , 0
       0                               0
Bank Sta=9783.196,10216.74
Exp/Cntr=0.3,0.1

Type RM Length L Ch R = 1 ,6645.216,98.509000,98.509000,98.509000
XS GIS Cut Line= 6
821531.130730645785548.010752529821662.370889814785653.066594428
821687.487305123785665.426408412821736.650828709785674.350318765
821770.944646112785687.867645583821897.269118148785773.832392935
#Sta/Elev= 30
 9782.06295.10829787.094293.9314 9808.62290.65459824.253287.84689839.132285.9099
 9855.52283.14079871.153282.37689886.786279.94059891.171279.5292 9902.42277.0097
9916.462274.58959928.805273.26429936.486272.07859964.322266.59239985.885 264.405
9996.062261.511910006.21261.971210016.37265.207710026.53264.484910030.32265.0716
10036.99266.615910047.62269.736910058.19272.323410081.52276.195610093.17276.9064
10098.09 276.88410117.52277.862610141.94278.416610166.37279.831910217.99285.8524
#Mann= 3 , 0 , 0
 9782.06   0.055       0 9782.06   0.055       010217.99   0.055       0
#XS Ineff= 2 , 0
       0                               0
Bank Sta=9782.06,10217.99
Exp/Cntr=0.3,0.1