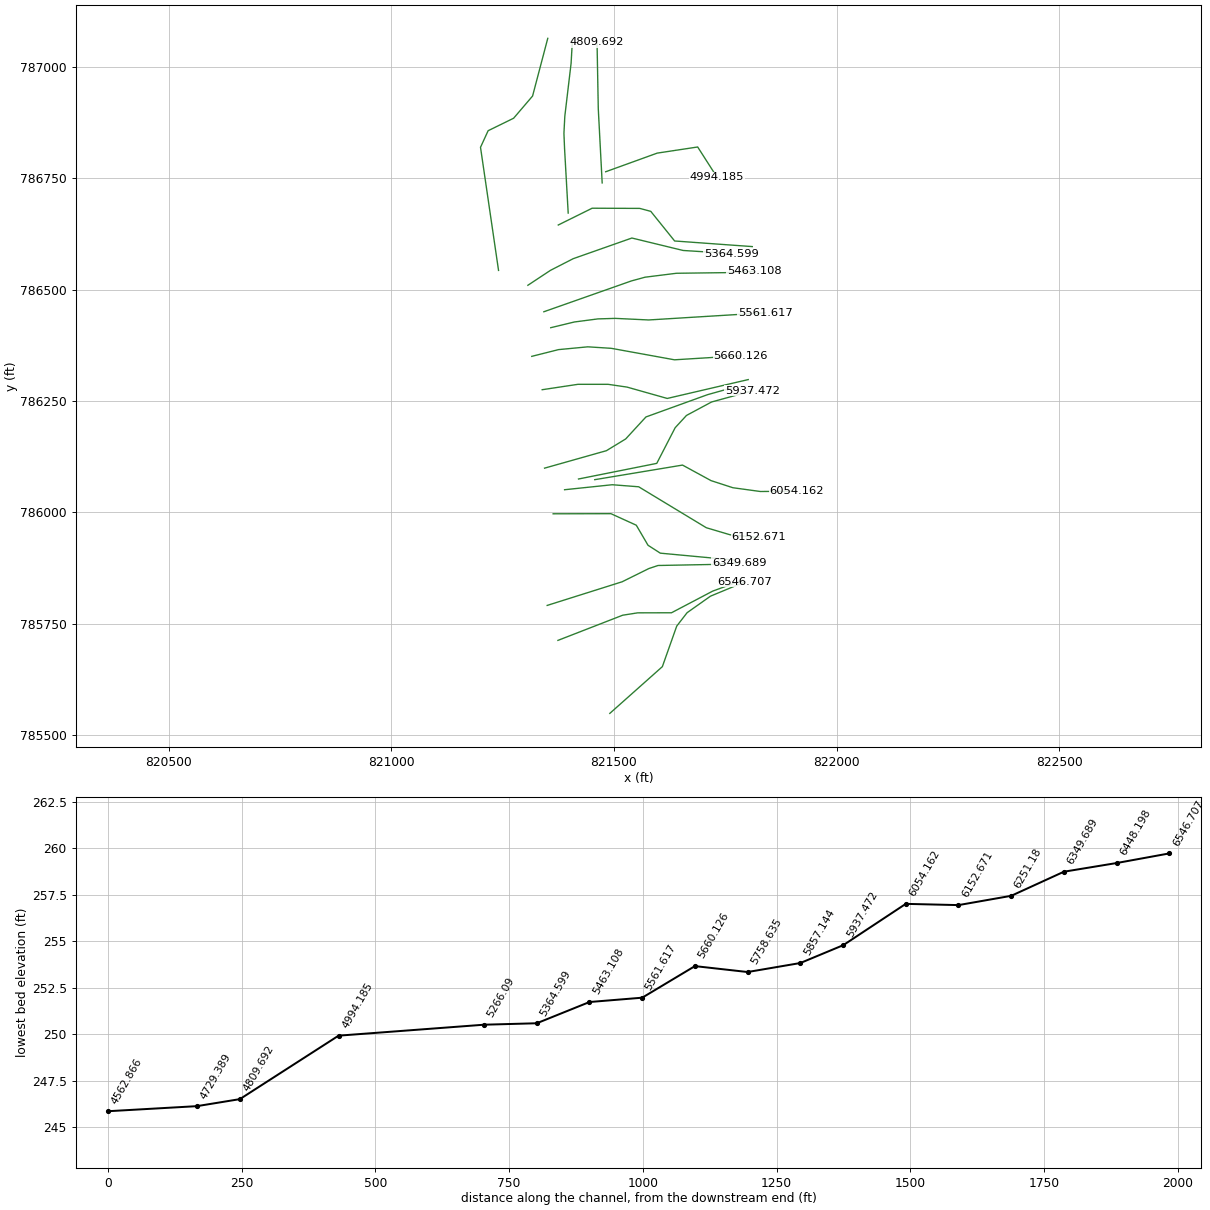
HEC-RAS study 17398_ras.prj: 17398

--- 17398_ras.g01 (geometry) --- (continued)

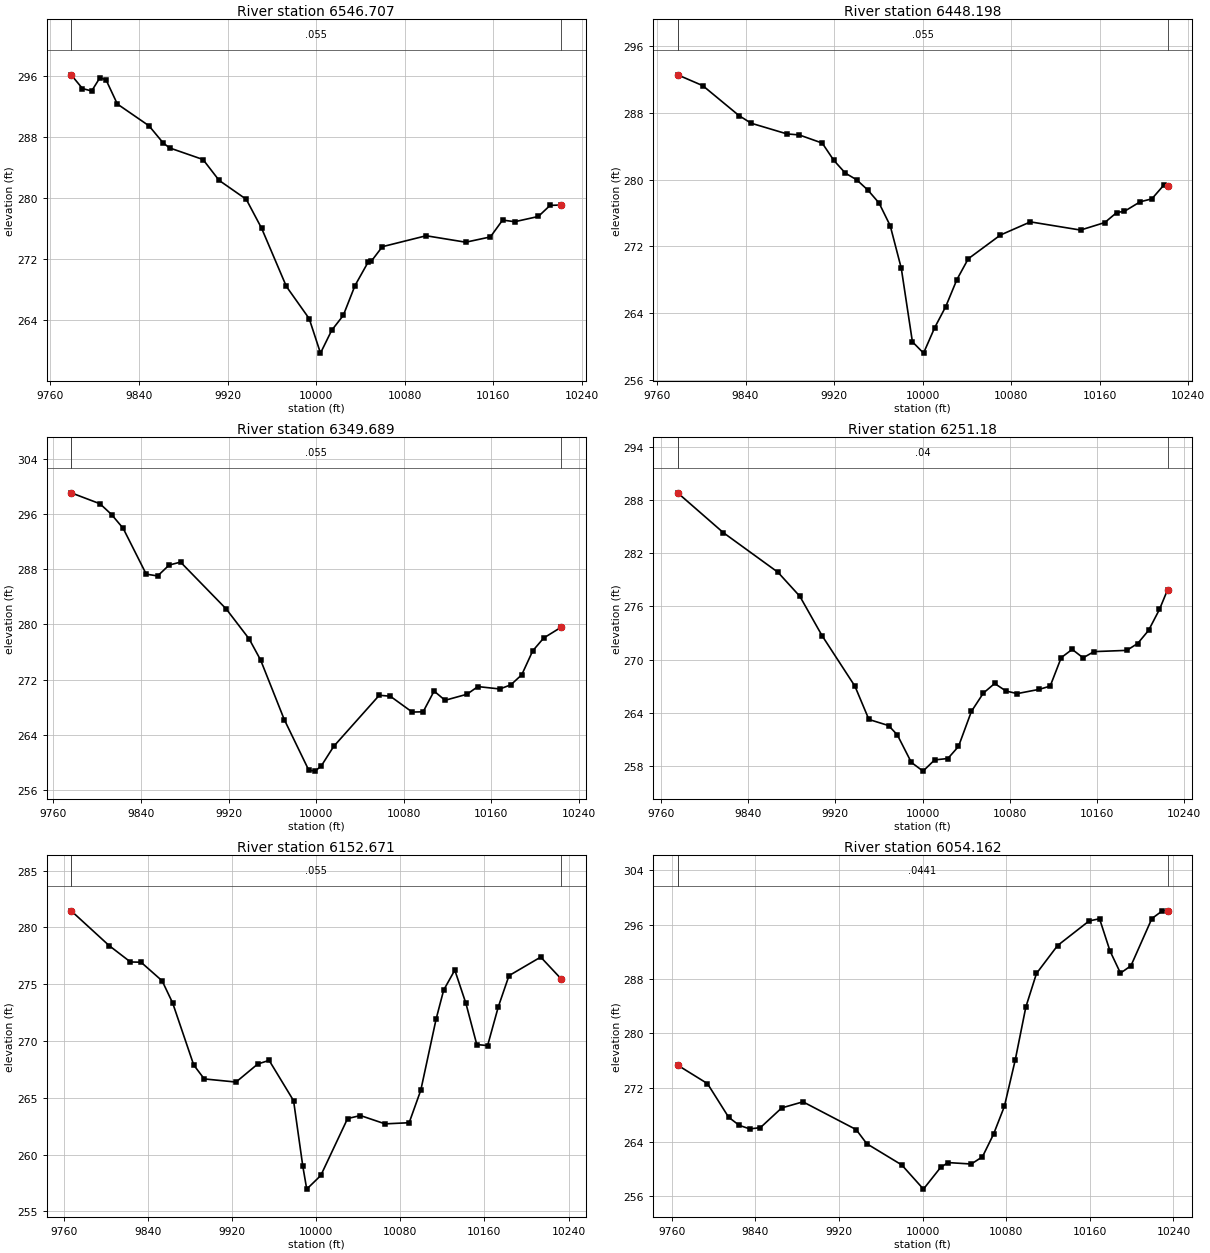
Type RM Length L Ch R = 1 ,6546.707,98.509000,98.509000,98.509000
XS GIS Cut Line= 6
 821490.70432846785548.505100302821608.663213629785653.410456316
821640.900798094785744.431285805821664.196184644785774.542764538
821716.848281158785811.722965972821794.306868073785843.830739229
#Sta/Elev= 30
 9778.73296.11079788.954294.3161 9797.24293.99769804.696  295.739810.189295.4668
9820.437292.29529849.033289.44669861.982287.18559867.662286.5559 9897.83285.0407
9912.341282.31639936.868279.84249950.798276.0394 9973.12268.44829993.716264.2445
10003.93259.734110014.09 262.72810024.49264.657310035.12268.570810046.79271.5855
10049.98 271.77910059.81273.646510099.37275.076410135.12274.232710157.37274.9225
10168.43277.126110179.38276.910110200.67277.595610211.32279.046410221.23279.0944
#Mann= 3 , 0 , 0
 9778.73   0.055       0 9778.73   0.055       010221.23   0.055       0
#XS Ineff= 2 , 0
       0                               0
Bank Sta=9778.73,10221.23
Exp/Cntr=0.3,0.1

Type RM Length L Ch R = 1 ,6448.198,98.509000,98.509000,98.509000
XS GIS Cut Line= 6
821374.193298826 785712.37910361821519.630048175785768.912518483
821553.454659652785774.233629891821629.152514711785774.381100625
821721.715519454785823.025334019821788.456470149785847.490396742
#Sta/Elev= 30
9778.715292.5535 9801.41291.25449834.132287.66969845.039286.76029877.516285.4731
9888.464285.35619909.301284.37729919.717282.32019930.132280.78359940.391279.9826
9950.514278.75279960.636277.19879970.741274.47429980.741 269.3739990.772260.5746
10000.84259.215710010.89262.264110020.93264.799810030.98268.029710041.23270.5177
10070.28273.360910097.39 274.93810142.67273.957710164.55274.857110175.36276.0581
10182.35276.205610196.53277.343410207.08 277.69410217.64279.306410221.29279.2243
#Mann= 3 , 0 , 0
9778.715   0.055       09778.715   0.055       010221.29   0.055       0
#XS Ineff= 2 , 0
       0                               0
Bank Sta=9778.715,10221.29
Exp/Cntr=0.3,0.1

Type RM Length L Ch R = 1 ,6349.689,98.508900,98.508900,98.508900
XS GIS Cut Line= 6
821350.064597715 785790.87344869821518.241083085785843.929169669
821578.453631802785873.708503198821598.924392107785880.531823262
821722.955904855785882.889767101821780.821150392785886.814933249
#Sta/Elev= 30
9776.275299.0483 9802.62297.46269813.185295.9025 9823.75  293.919844.823287.2743
9855.267287.01349865.711288.58539876.155289.01789917.931282.21929938.819277.8906
9949.263274.83859970.872266.21449993.229258.8938    9999258.748510004.65259.4948
10015.98262.322810057.62269.732910067.67269.597610087.69267.300610097.69267.3399
10107.69270.339710117.69269.005910137.69269.879410147.69270.991110167.69270.6457
10177.72 271.24210187.74272.699510197.76276.168210207.79278.026310223.64279.5785
#Mann= 3 , 0 , 0
9776.275   0.055       09776.275   0.055       010223.64   0.055       0
#XS Ineff= 2 , 0
       0                               0
Bank Sta=9776.275,10223.64
Exp/Cntr=0.3,0.1

Type RM Length L Ch R = 1 , 6251.18,98.509000,98.509000,98.509000
XS GIS Cut Line= 6
821363.411654223785996.592055303 821493.21250607785996.852103965
821550.112219591 785970.97411399821576.493839497785925.925929945
821604.063658995785908.215172549821772.450886633785892.499947541
#Sta/Elev= 30
9775.289288.78979817.187284.30549867.246279.84939887.376277.13849907.735272.7105
9937.934267.01069950.729263.26879968.791262.58079976.806261.53389989.655 258.435
 10000.4257.450410011.06258.714110023.17 258.87110032.93260.228310044.76264.1726
10055.77266.2414 10066.1267.319510076.44266.474810086.78266.180110106.97266.6586
10117.06267.025810127.16270.227610137.22271.161510147.23270.209110157.24270.9082
10187.28271.048210197.28271.820710207.28273.293410217.29275.656810224.74277.8696
#Mann= 3 , 0 , 0
9775.289    0.04       09775.289    0.04       010224.74    0.04       0
#XS Ineff= 2 , 0
       0                               0
Bank Sta=9775.289,10224.74
Exp/Cntr=0.3,0.1

Type RM Length L Ch R = 1 ,6152.671,98.509000,98.509000,98.509000
XS GIS Cut Line= 6
821389.122056053786050.630543903821496.122485631786061.836850147
821555.487083055786057.238147651821707.265253438785965.342735869
821760.883465798785949.444519288821824.318395433785943.398781009
#Sta/Elev= 30
9767.161281.4659 9803.35278.39519823.523276.96119833.573276.93949853.622275.2999
9863.647 273.3479883.674267.88399893.675 266.6599923.881266.38229944.507  267.97
9955.341268.2937 9978.59264.74089987.392258.95389991.103 256.95110004.45258.1519
10029.94263.167110042.15263.432910065.56262.699910088.47262.800410099.53265.6668
10114.14271.951310121.28274.484810131.86276.244410142.44273.305510152.76269.6861
10163.04269.596410173.25273.021510183.36275.753910213.53277.391710232.88275.4784
#Mann= 3 , 0 , 0
9767.161   0.055       09767.161   0.055       010232.88   0.055       0
#XS Ineff= 2 , 0
       0                               0
Bank Sta=9767.161,10232.88
Exp/Cntr=0.3,0.1

Type RM Length L Ch R = 1 ,6054.162,116.689200,116.689200,116.689200
XS GIS Cut Line= 6
821456.844238097786073.212211481821653.923101604786105.968874734
821717.960018773786071.059080899821766.985940315786055.129283667
821828.611514141786046.651605288821910.013891741786047.344903891
#Sta/Elev= 30
9765.749275.29289794.259272.5736 9814.51267.61519824.635 266.4259834.761265.8959
9844.892266.08479865.245268.98889885.598269.89019936.482265.79669946.638263.7119
9980.106260.583710000.84257.017510017.25260.214910024.38260.931910046.58260.7193
10057.29261.786810067.88 265.11310078.24269.2067 10088.6276.0236 10098.8283.8665
10108.97288.817510129.17292.9336 10159.3296.5574 10169.3296.8786 10179.3292.1262
 10189.3288.864210199.31289.943210219.33296.905310229.34 298.04910234.36298.0106
#Mann= 3 , 0 , 0
9765.749  0.0441       09765.749  0.0441       010234.36  0.0441       0
#XS Ineff= 2 , 0
       0                10022.39       0
Bank Sta=9765.749,10234.36
Exp/Cntr=0.3,0.1

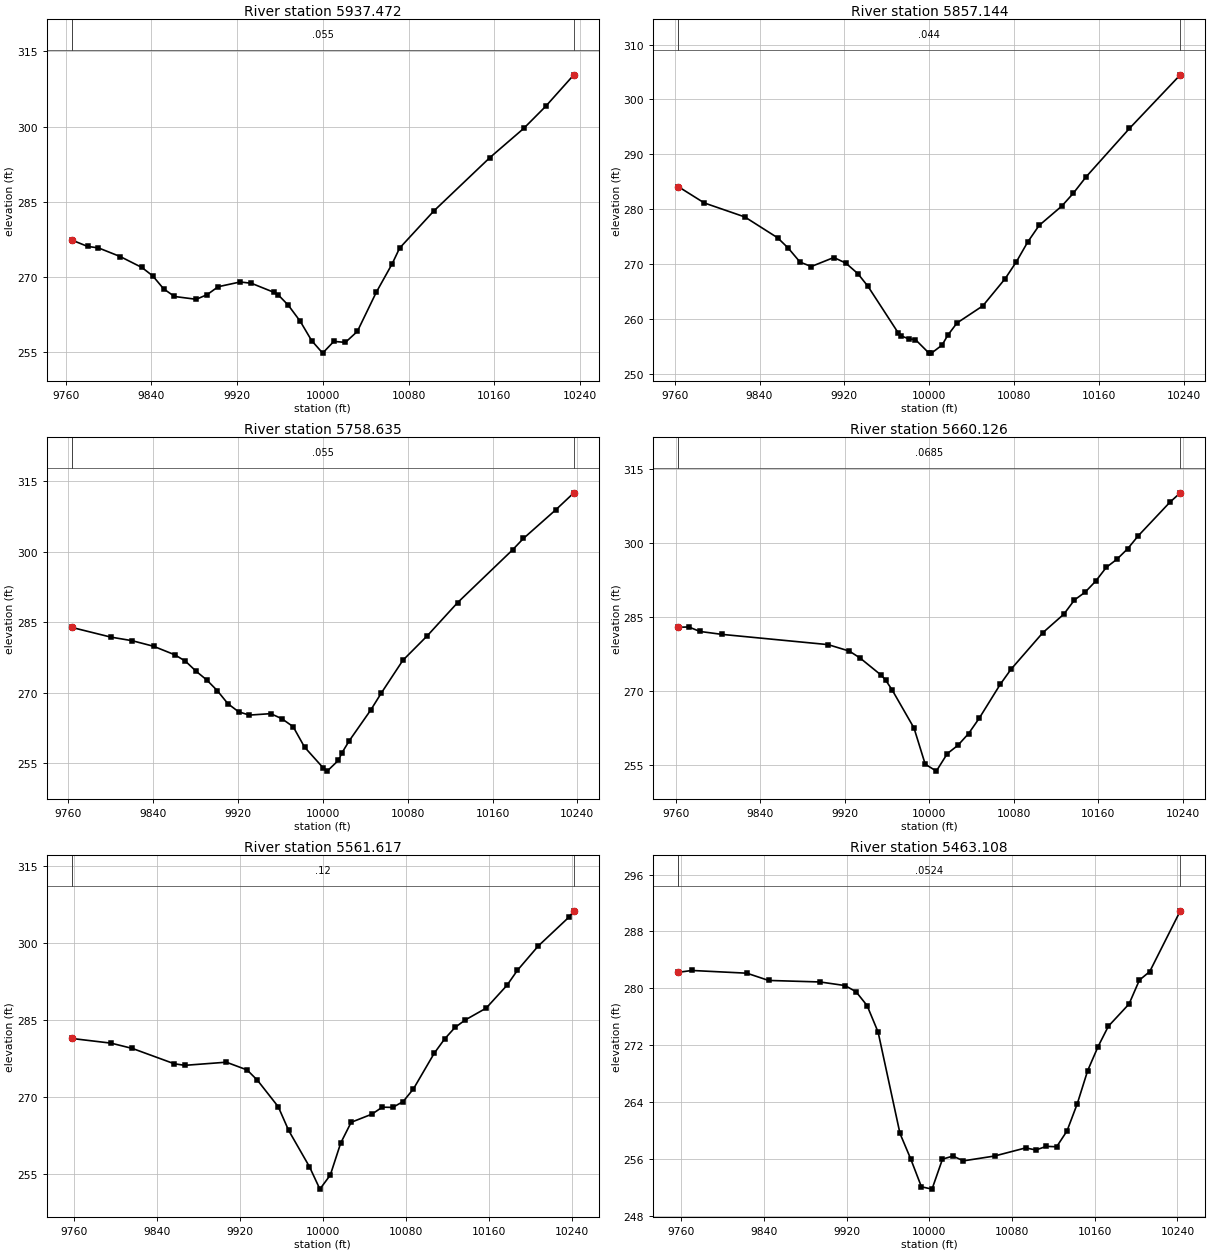
Type RM Length L Ch R = 1 ,5937.472,80.328800,80.328800,80.328800
XS GIS Cut Line= 6
821420.438676299786074.719348247821596.099464262  786109.8148968
821637.320988493786189.698707545821662.754674188786217.369787492
821719.101116411786247.603008053821810.591143725786272.699478555
#Sta/Elev= 30
9765.689277.3535 9780.45276.08139790.587275.7852 9810.86274.06369831.134271.8776
9841.271270.19939851.408267.62049861.545266.09369881.819265.53319892.019266.4606
9902.279268.04139922.799268.98829933.287268.73179954.122266.94099958.486266.3833
9967.699264.36229978.905261.13929989.465257.3102 9999.79254.7955 10010.2257.1336
10021.01256.938410032.16259.1249 10049.8266.919310064.67272.618710071.58275.7367
10103.47283.136110155.93293.818310187.35 299.607 10207.9304.023410234.19310.3099
#Mann= 3 , 0 , 0
9765.689   0.055       09765.689   0.055       010234.19   0.055       0
#XS Ineff= 2 , 0
       0                               0
Bank Sta=9765.689,10234.19
Exp/Cntr=0.3,0.1

Type RM Length L Ch R = 1 ,5857.144,98.509000,98.509000,98.509000
XS GIS Cut Line= 6
821344.143361398786099.068410363821483.037075575786138.279859302
821526.305540331 786164.61812751821571.807090018786214.016184158
821710.034994322786264.025283114821771.150999273786281.106619185
#Sta/Elev= 30
9763.368284.14039787.929281.16569826.081278.62359857.022274.82849866.959272.9703
 9878.17270.40459888.744269.59519910.032271.23739921.318270.21799932.604268.3097
9942.182265.99379970.795257.49269973.409256.97779980.727256.41979986.867256.3101
9999.465253.875810002.04253.832210012.02255.288410017.44 257.09410026.09259.3159
10050.46262.439210071.48267.3786 10082.1270.464810092.81274.072510103.51277.0746
10124.92280.604610135.63282.907210147.84285.929110188.67294.732510236.59304.4888
#Mann= 3 , 0 , 0
9763.368   0.044       09763.368   0.044       010236.59   0.044       0
#XS Ineff= 2 , 0
       0                               0
Bank Sta=9763.368,10236.59
Exp/Cntr=0.3,0.1

Type RM Length L Ch R = 1 ,5758.635,98.508900,98.508900,98.508900
XS GIS Cut Line= 6
821338.870383694 786275.18857339 821419.03937939786287.284215962
821487.186311731786287.239910415821529.379510072786281.054603787
821619.629587696786255.579907681821801.425801372786297.911246946
#Sta/Elev= 30
9763.393283.8873 9800.19281.82799820.349281.06199840.471279.87939860.507278.0674
9870.515276.71789880.521274.58689890.526272.74219900.532 270.4629910.537267.6797
9920.622265.96249930.729265.25259950.943 265.561 9961.38264.48969972.074262.7914
9982.769258.467310000.57253.993310004.14253.3478 10014.7255.631210018.13257.2612
10025.02259.821710045.21266.327310055.27 269.977 10075.5 276.896 10098.6282.1325
 10127.2 289.17910178.87300.359810189.11302.782610219.84308.921110236.66312.4854
#Mann= 3 , 0 , 0
9763.393   0.055       09763.393   0.055       010236.66   0.055       0
#XS Ineff= 2 , 0
       0                               0
Bank Sta=9763.393,10236.66
Exp/Cntr=0.3,0.1

Type RM Length L Ch R = 1 ,5660.126,98.509000,98.509000,98.509000
XS GIS Cut Line= 6
821315.461628991786350.069432588 821375.36303095786365.173042611
821441.253759023786371.462911752821493.933639484786368.114947136
821635.952570175786342.331975558821784.662766972786351.486576921
#Sta/Elev= 30
9762.459282.90029772.416282.97729782.854282.06489803.424281.47429904.271279.3815
9924.312278.06799934.365276.68079954.643273.14369958.861 272.1149964.851270.1664
9985.538262.42189996.105255.093410006.65253.666110017.05257.227910027.09258.9153
10037.14261.292910047.19264.399210067.28271.358310077.33274.377510107.38281.7974
10127.38285.590210137.38 288.46810147.38290.031810157.43292.284210167.48295.0872
10177.53296.738110187.58298.846710197.63301.484510227.79308.3584 10237.5310.2401
#Mann= 3 , 0 , 0
9762.459  0.0685       09762.459  0.0685       0 10237.5  0.0685       0
#XS Ineff= 2 , 0
       0                               0
Bank Sta=9762.459,10237.5
Exp/Cntr=0.3,0.1

Type RM Length L Ch R = 1 ,5561.617,98.509000,98.509000,98.509000
XS GIS Cut Line= 6
821358.067990913786414.425008844    821411.09001786427.249847562
821463.949807183786434.153947109821502.783523105786435.337666597
821577.944716846786431.788236499821839.218830702786447.845508591
#Sta/Elev= 30
9758.142 281.3139796.139280.39699816.637279.36189856.976276.38089867.053276.0783
9907.073  276.699927.095275.18039937.106273.16139957.129268.0057 9967.14263.3934
9987.184256.32499997.225251.965610007.26254.7062 10017.3260.946910027.34264.9789
10047.37266.571510057.37267.933210067.38267.880510077.39269.0127 10087.4271.4937
10107.41278.433610117.42 281.21610127.43283.461810137.43284.930310157.45 287.221
10177.49291.664610187.53294.5795 10207.6299.316510237.71305.040710241.94306.1754
#Mann= 3 , 0 , 0
9758.142    0.12       09758.142    0.12       010241.94    0.12       0
#XS Ineff= 2 , 0
       0                               0
Bank Sta=9758.142,10241.94
Exp/Cntr=0.3,0.1

Type RM Length L Ch R = 1 ,5463.108,98.509000,98.509000,98.509000
XS GIS Cut Line= 6
821342.628502994786450.212503514821539.071026776786519.378627821
 821569.82061178786527.788304388821640.399849253786536.617588409
821749.828578485 786537.99889661 821814.53181558786541.066638847
#Sta/Elev= 30
 9757.22282.24349770.474282.50919823.583282.12529844.617281.10579894.395280.8895
9918.559280.38419929.218279.50949939.877277.56719950.536273.83019971.682 259.569
9982.049255.98839992.416252.061110002.66251.732910012.78255.953810022.89 256.385
10033.01255.711210063.16256.392110093.18257.533510103.19257.244210113.19257.7523
10123.19257.696510133.19259.915410143.19263.768110153.19268.406310163.19271.7723
10173.19274.652610193.21277.788610203.22281.150310213.23282.3539 10242.8290.9033
#Mann= 3 , 0 , 0
 9757.22  0.0524       0 9757.22  0.0524       0 10242.8  0.0524       0
#XS Ineff= 2 , 0
       0                10022.36       0
Bank Sta=9757.22,10242.8
Exp/Cntr=0.3,0.1

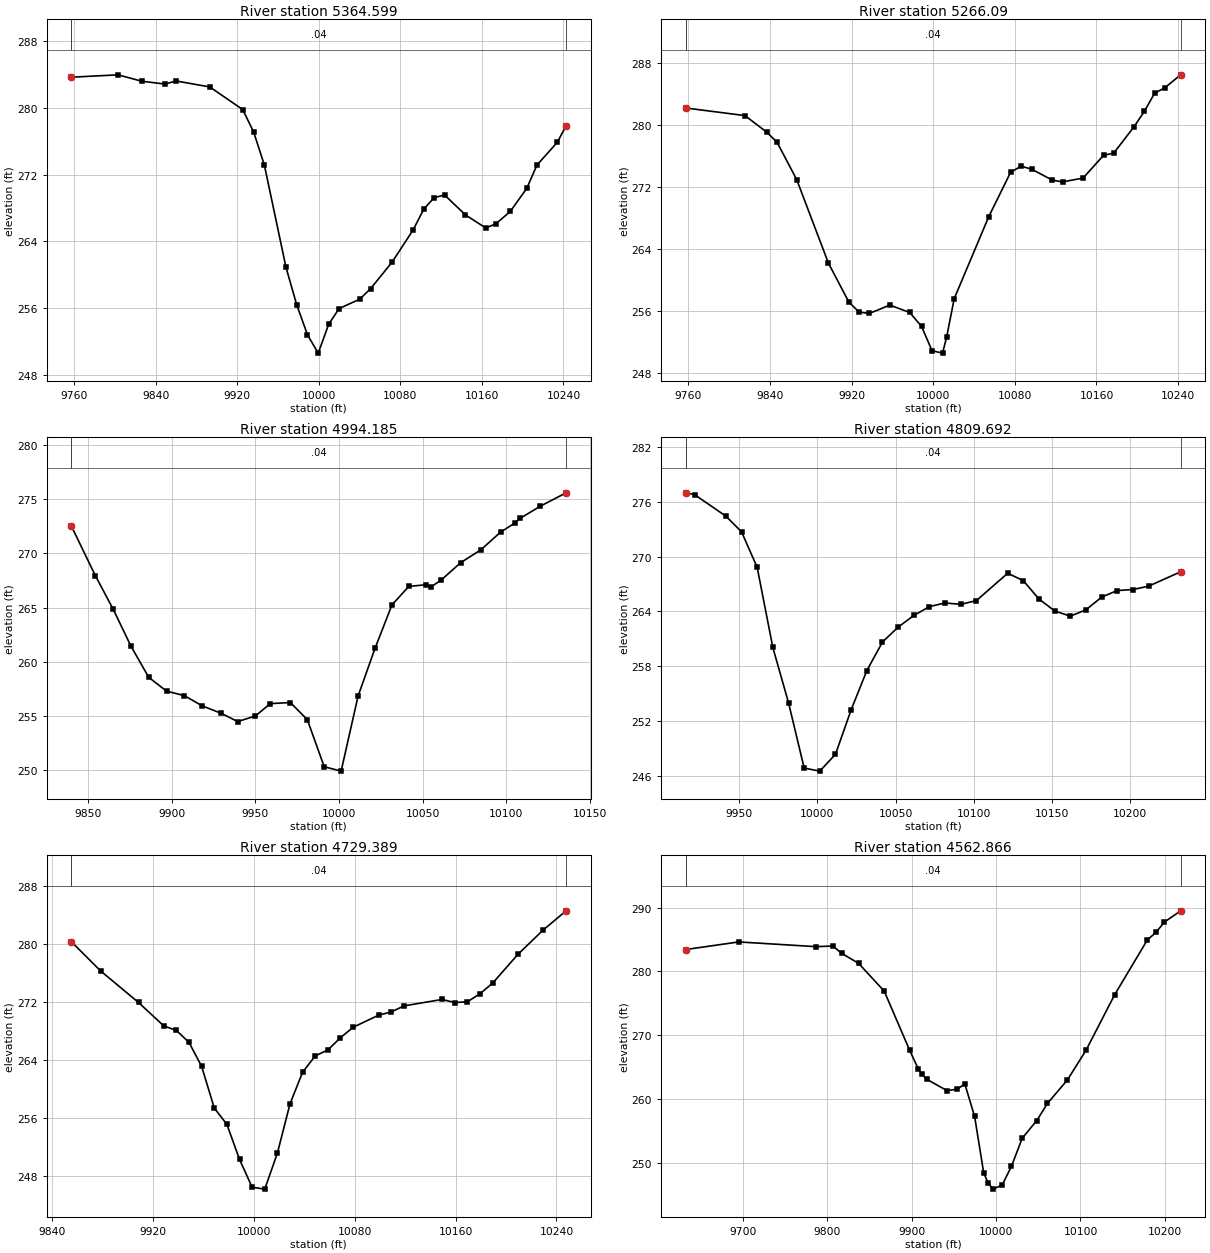
Type RM Length L Ch R = 1 ,5364.599,98.509000,98.509000,98.509000
XS GIS Cut Line= 6
 821306.72064452786509.674230758821357.399115512786543.153258456
821408.442973178786569.334293337821540.232243196786615.737209131
821655.257771909786587.811706189821763.592416406 786580.92269388
#Sta/Elev= 30
9757.254283.67959803.132283.96589826.534283.19539849.012282.8601 9860.25283.2271
9893.152282.51059925.394279.80079936.131277.11619946.694273.12479967.821260.8994
9978.384256.38639988.948252.78429999.476 250.58910009.79254.057910019.97255.9349
 10040.3257.067310050.81258.320510071.81261.476110092.73265.395710102.97 267.846
10113.21  269.2410123.45269.552410143.75 267.18110163.86265.595610173.92266.1129
10187.91267.584110204.01270.343710214.01273.137310234.01275.875110242.61277.8486
#Mann= 3 , 0 , 0
9757.254    0.04       09757.254    0.04       010242.61    0.04       0
#XS Ineff= 2 , 0
       0                               0
Bank Sta=9757.254,10242.61
Exp/Cntr=0.3,0.1

Type RM Length L Ch R = 1 , 5266.09,271.904900,271.904900,271.904900
XS GIS Cut Line= 6
821375.011727165786644.992747515821450.993822609786682.657513943
821557.856354931786682.267185107821582.658562723786675.610229781
821636.212800803 786609.09110502821810.557407567786596.503188167
#Sta/Elev= 30
9757.491282.18149815.366 281.2029836.586279.08289846.892277.75229866.198272.9092
9897.171262.15619917.223 257.1139927.249255.81559937.276255.63619957.393 256.717
9976.949255.76269988.529253.96479998.771 250.82110009.09250.511210013.09252.5719
10020.51257.541310054.46268.163610075.86273.882910086.16274.666310096.47 274.275
10116.74272.859110126.81272.637710146.91273.130910166.92276.063410176.93276.3533
10196.94279.786410206.95281.752210216.96284.091710226.97284.792710242.54 286.469
#Mann= 3 , 0 , 0
9757.491    0.04       09757.491    0.04       010242.54    0.04       0
#XS Ineff= 2 , 0
       0                               0
Bank Sta=9757.491,10242.54
Exp/Cntr=0.3,0.1

Type RM Length L Ch R = 1 ,4994.185,184.493200,184.493200,184.493200
XS GIS Cut Line= 4
821481.458066821786764.546726108821597.106693506786806.370339021
821687.967515916786820.135253325821731.573087245786752.001548052
#Sta/Elev= 30
9839.993272.54029854.394267.94799865.027264.85949875.661261.44919886.295258.5712
9896.929257.29969907.563256.88659918.197255.94569929.539 255.2599939.464254.4917
9950.098255.01229958.943256.14659970.956256.2483 9981.07 254.6769991.184 250.327
 10001.3249.921210011.41256.836810021.53261.236110031.64265.244410041.75 266.959
10051.87267.108810054.87266.897410060.97267.526310072.84269.159310084.71270.3193
10096.58271.960810105.02272.790410108.46273.251610120.33274.355110135.76275.5902
#Mann= 3 , 0 , 0
9839.993    0.04       09839.993    0.04       010135.76    0.04       0
#XS Ineff= 2 , 0
       0                               0
Bank Sta=9839.993,10135.76
Exp/Cntr=0.3,0.1

Type RM Length L Ch R = 1 ,4809.692,80.303100,80.303100,80.303100
XS GIS Cut Line= 3
821473.532364389786739.488301144821464.797556041786905.900307922
821462.000412671787055.547478093
#Sta/Elev= 30
9915.929 276.9959921.448276.80289941.476 274.443 9951.49272.72899961.503268.8312
9971.517260.04949981.531254.00719991.545 246.83910001.56 246.50410011.57248.3544
10021.59253.2247 10031.6257.520110041.61260.645510051.63262.281810061.64263.5575
10071.65264.530510081.67264.929910091.67264.775910101.67265.190510121.68268.1893
10131.68 267.36210141.68265.352810151.68264.058710161.68263.482610171.69264.1776
10181.69 265.56510191.69266.291210201.69266.397810211.69 266.76810232.24268.3427
#Mann= 3 , 0 , 0
9915.929    0.04       09915.929    0.04       010232.24    0.04       0
#XS Ineff= 2 , 0
       0                               0
Bank Sta=9915.929,10232.24
Exp/Cntr=0.3,0.1

Type RM Length L Ch R = 1 ,4729.389,166.523000,166.523000,166.523000
XS GIS Cut Line= 6
 821397.24335381786671.761541038 821389.04431164786817.396953483
821387.676302502786850.851108508821389.652298644786889.088195062
821403.719360958787007.730817636821406.918309892787063.015041105
#Sta/Elev= 30
9855.133 280.3149878.408276.26169908.454271.91049928.486268.67229938.501268.0439
9948.517266.39429958.532263.07729968.548257.32729978.564255.07419988.579250.2338
9998.595246.388310008.61246.125810018.62251.096810028.63257.907210038.64 262.276
10048.65264.528610058.66265.347910068.68267.045710078.72268.483910098.86270.1482
10108.93270.6025   10119271.433910149.21272.324410159.28271.896510169.35272.0032
10179.42273.124310189.49274.602210209.54 278.57710229.58281.934110247.62284.5666
#Mann= 3 , 0 , 0
9855.133    0.04       09855.133    0.04       010247.62    0.04       0
#XS Ineff= 2 , 0
       0                               0
Bank Sta=9855.133,10247.62
Exp/Cntr=0.3,0.1

Type RM Length L Ch R = 1 ,4562.866,249.519900,249.519900,249.519900
XS GIS Cut Line= 6
 821240.85309032786543.039555726821200.377578232786819.421624045
821217.482270375786856.669514511821274.705440769786884.688838123
821317.273940082786934.545417494821351.385160818787064.077876496
#Sta/Elev= 30
9632.249283.42549694.919284.61339786.292 283.8759806.597283.9677 9816.75282.8424
9837.055281.24899867.417 276.8879897.523267.62329907.523 264.7679911.945263.8937
9917.652263.08369941.805261.3036 9953.97261.5219 9962.91262.34859974.532257.2555
9985.333248.38199990.755246.77699996.168245.852410007.18246.491210018.24249.4381
10030.98253.837210048.27256.613310060.91259.2963 10084.6262.989410106.59267.6225
10140.46 276.31310179.31284.930810189.42286.097410199.53 287.73110218.81289.4908
#Mann= 3 , 0 , 0
9632.249    0.04       09632.249    0.04       010218.81    0.04       0
#XS Ineff= 2 , 0
       0                               0
Bank Sta=9632.249,10218.81
Exp/Cntr=0.3,0.1