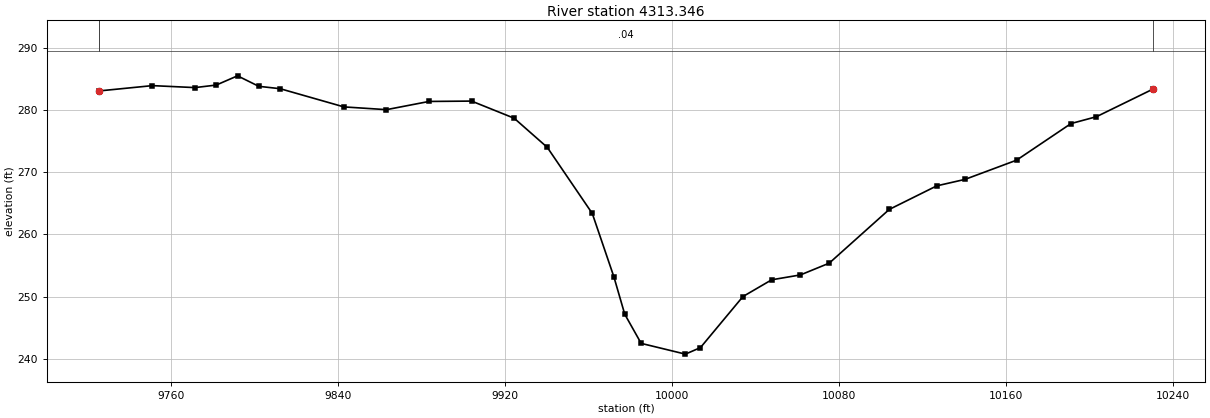
HEC-RAS study 17398_ras.prj: 17398

--- 17398_ras.g01 (geometry) --- (continued)

Type RM Length L Ch R = 1 ,4313.346,0.000000,0.000000,0.000000
XS GIS Cut Line= 6
821190.843753278786530.005212575821148.880506968786740.555765537
821119.870631693786775.078036383821045.627387691786846.365870873
821003.020684303786893.418538333820957.828438068786957.695522383
#Sta/Elev= 30
9725.458283.04229750.945283.89299771.338283.57619781.535283.98359791.732285.4666
9801.928283.78179812.125283.39989842.715280.47569863.108280.03279883.502281.3519
9903.895281.40969924.288278.6574 9940.15  273.989961.726263.35729972.079253.1788
 9977.27247.18259985.141242.494510006.34240.767110013.55241.812710033.91250.0145
10047.69252.707110061.48253.490210075.26255.379310104.01264.004710126.81267.7969
 10140.3268.831110165.04271.919510191.11277.798510203.31 278.90210230.28 283.317
#Mann= 3 , 0 , 0
9725.458    0.04       09725.458    0.04       010230.28    0.04       0
#XS Ineff= 2 , 0
       0                               0
Bank Sta=9725.458,10230.28
Exp/Cntr=0.3,0.1